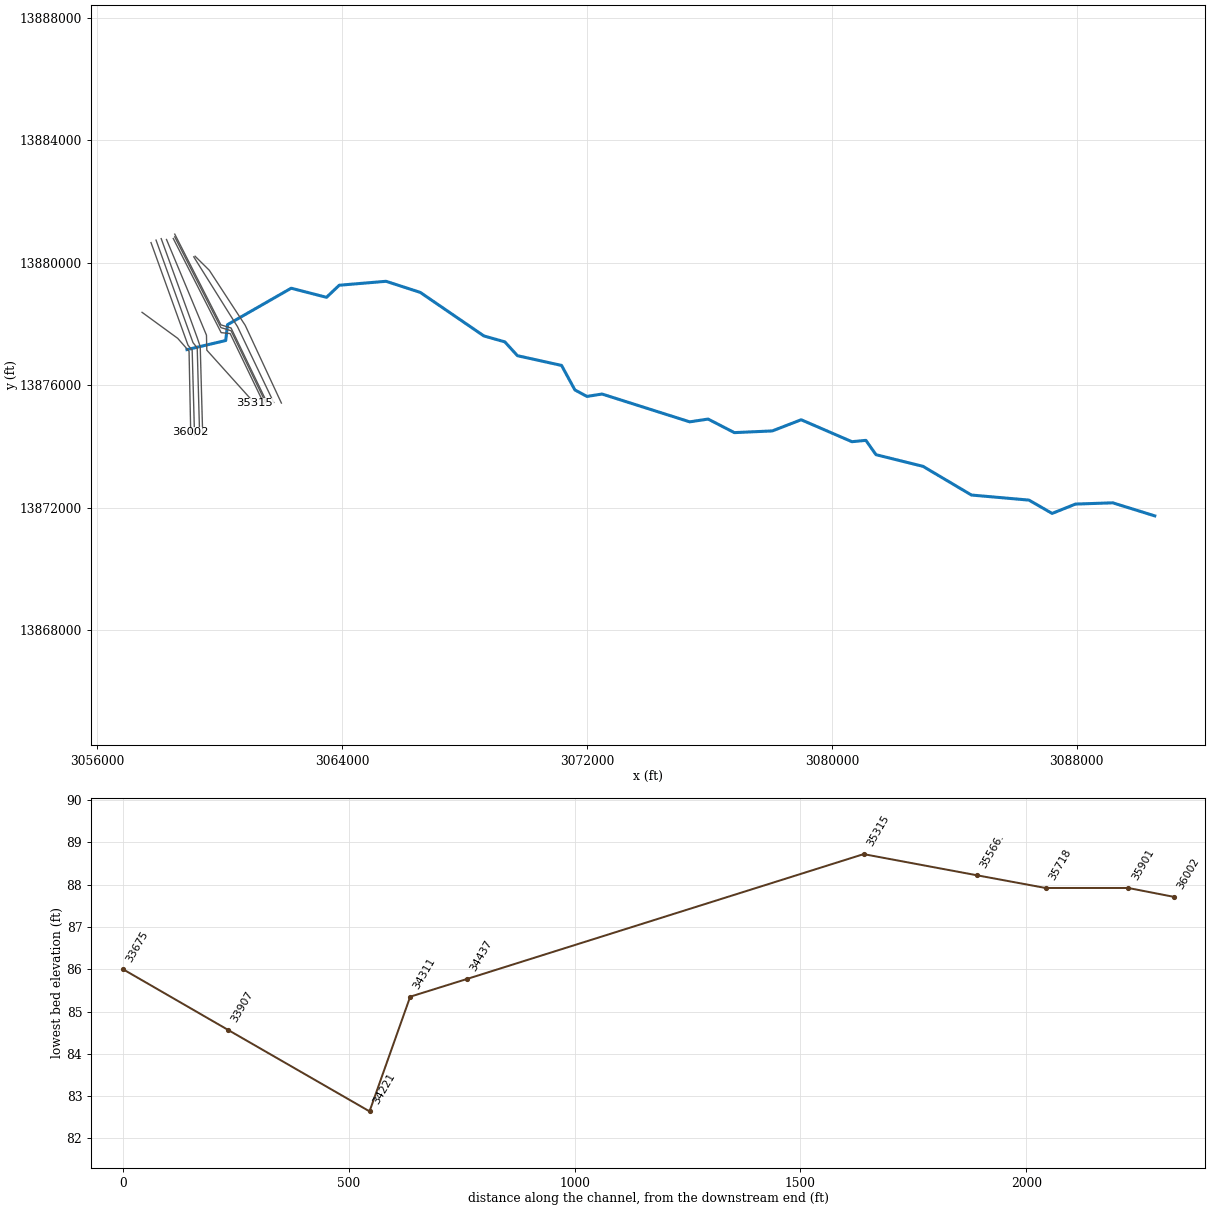
--- E117-00-00.prj (project) ---

Proj Title=E117-00-00
Current Plan=p07
Default Exp/Contr=.3,.1
English Units
Geom File=g02
Geom File=g01
Flow File=f01
Flow File=f02
Plan File=p07
Plan File=p05
Y Axis Title=Elevation
X Axis Title(PF)=Main Channel Distance
X Axis Title(XS)=Station
BEGIN DESCRIPTION:
White Oak Bayou Watershed
Cole Creek
HCFCD Unit E117-00-00
Flood Hazard Model
10, 2, 1, 0.2%
Filename E117-00-00
Prepared by:  Mason Liebau  DATE:  March 10, 2004
Reviewed by:  _____________________  DATE:  __________________
STATUS (Final)
END DESCRIPTION:
DSS File=dss
DSS Export Rating Curves= 0
DSS Export Rating Curve Sorted= 0
DSS Export Volume Flow Curves= 0
DXF OffsetX= 0
DXF OffsetY= 0
DXF ScaleX= 1
DXF ScaleY= 10

--- E117-00-00.p07 (plan) ---

Plan Title=FEMA Effective June 2007
Version=Version 3.0.1  Mar 2001
Short Identifier=FEMAeff0607
Geom File=g02
Flow File=f01
Subcritical Flow
K Sum by GR= 0
Std Step Tol= 0.01
Critical Tol= 0.01
Num of Std Step Trials= 20
Max Error Tol= 0.3
Flow Tol Ratio= 0.001
Split Flow NTrial= 30
Split Flow Tol= 0.02
Split Flow Ratio= 0.02
Log Output Level= 0
Friction Slope Method= 1
Unsteady Friction Slope Method= 2
Parabolic Critical Depth
Global Vel Dist= 0 , 0 , 0
Global Log Level= 0
CheckData=True
Encroach Param=-1 ,0,0, 0
BEGIN DESCRIPTION:
Revised
END DESCRIPTION:
Computation Interval=1HOUR
Output Interval=1HOUR
Run HTab= 0
Run UNet= 0
Run PostProcess= 0
UNET Theta= 1
UNET ZTol= 0.02
UNET ZSATol= 0.1
UNET MxIter= 20
UNET MaxInSteps= 20
UNET DtIC= 0
UNET DtMin= 0
UNET MaxCRTS= 20
UNET WFStab= 2
UNET SFStab= 1
UNET WFX= 1
UNET SFX= 1
UNET Convert EG Bridges=-1
UNET Use Existing IB Tables=-1
Instantaneous Interval=1HOUR
Write IC File= 0
IC Time=0
Write Velocity= 0
Write Detailed= 0

--- E117-00-00.p05 (plan) ---

Plan Title=Floodway
Version=Version 3.0.1  Mar 2001
Short Identifier=Floodway0607
Geom File=g02
Flow File=f02
Subcritical Flow
K Sum by GR= 0
Std Step Tol= 0.01
Critical Tol= 0.01
Num of Std Step Trials= 20
Max Error Tol= 0.3
Flow Tol Ratio= 0.001
Split Flow NTrial= 30
Split Flow Tol= 0.02
Split Flow Ratio= 0.02
Log Output Level= 0
Friction Slope Method= 1
Unsteady Friction Slope Method= 2
Parabolic Critical Depth
Global Vel Dist= 0 , 0 , 0
Global Log Level= 0
CheckData=True
Encroach Param=-1 ,0,0, 2
Encroach River=E117-00-00
Encroach Reach=Reach - 1
Encroach Node=36002
       1 4889.75    5080
Encroach Node=35901
       1 3464.54    3594
Encroach Node=35811
       1 3464.543563.323
Encroach Node=35718
       1 3464.543563.323
Encroach Node=35566.
       1  4958.1  5043.2
Encroach Node=35315
       1  4958.1    5076
Encroach Node=34437
       1  4849.4  5149.4
Encroach Node=34311
       1 4749.95 5249.95
Encroach Node=34267
       1 4749.95 5249.95
Encroach Node=34221
       1 4749.95 5249.95
Encroach Node=33907
       1 4751.15 5251.15
Encroach Node=33675
       1 4751.15 5251.15
Encroach Node=32920
       1 4750.65 5250.65
Encroach Node=32902
       1 4751.45 5251.45
Encroach Node=32836
       1 4748.52 5248.52
Encroach Node=32825.5
       1 4748.52 5248.52
Encroach Node=32811
       1 4748.52 5248.52
Encroach Node=32762
       1    4970    5040
Encroach Node=32747.5
       1    4970    5040
Encroach Node=32734
       1    4970    5040
Encroach Node=32700
       1    4970    5040
Encroach Node=32652
       1    4970    5040
Encroach Node=32602
       1    4970    5040
Encroach Node=32588
       1 4752.65 5252.65
Encroach Node=31272
       1 4752.65 5252.65
Encroach Node=29956
       1 4752.65 5252.65
Encroach Node=29929
       1 4752.65 5252.65
Encroach Node=29890.5
       1 4752.65 5252.65
Encroach Node=29852
       1 4752.65 5252.65
Encroach Node=29805
       1 3348.15 3712.31
Encroach Node=29680
       1 3348.15 3712.31
Encroach Node=29551
       1 3245.62  3641.6
Encroach Node=29500
       1 3228.96 3628.61
Encroach Node=29462
       1 3228.96 3628.61
Encroach Node=29416
       1 3228.96 3628.61
Encroach Node=29094
       1  4961.6    5140
Encroach Node=28999.5
       1  4961.6    5140
Encroach Node=28897
       1    4950    5037
Encroach Node=28684
       1    4970    5037
Encroach Node=28302
       1    4970    5037
Encroach Node=27886
       1    4875    5050
Encroach Node=27836
       1    4800    5200
Encroach Node=27778
       1    4935    5050
Encroach Node=27568
       1    4935    5035
Encroach Node=27267
       1    4750    5045
Encroach Node=25938
       1 4697.55 5297.55
Encroach Node=24962
       1  4834.6  5174.6
Encroach Node=24075
       1 4828.75 5168.75
Encroach Node=23347
       1 4818.75 5178.75
Encroach Node=22996
       1  4852.8  5152.8
Encroach Node=22931
       1  4921.9  5140.3
Encroach Node=22854
       1  4877.8  5127.8
Encroach Node=22615
       1 4865.45 5115.45
Encroach Node=22223
       1 4865.45 5115.45
Encroach Node=21280
       1 4895.15 5095.15
Encroach Node=20308
       1  4900.8  5100.8
Encroach Node=19566
       1    4915    5085
Encroach Node=19349
       1 4928.85 5078.85
Encroach Node=19322
       1  4925.2  5057.5
Encroach Node=19290
       1  4925.2  5057.5
Encroach Node=19077
       1    4952  5057.5
Encroach Node=18678
       1  4933.3  5055.7
Encroach Node=17828
       1  4926.5 5059.45
Encroach Node=17658
       1  4922.5  5057.7
Encroach Node=17630
       1  4922.5  5057.7
Encroach Node=17597
       1  4922.5  5060.1
Encroach Node=17414
       1    4920    5057
Encroach Node=16773
       1  4929.1  5079.1
Encroach Node=16140
       1  4903.6  5129.1
Encroach Node=15781
       13434.1113637.727
Encroach Node=15698
       13434.1113637.727
Encroach Node=15619
       13434.1113637.727
Encroach Node=15364
       1 4890.34  5122.4
Encroach Node=15001
       1  4874.7 5115.73
Encroach Node=14709
       1 3713.26 3953.26
Encroach Node=14698.5
       1 3714.51 3952.01
Encroach Node=14681
       1 3715.76 3950.76
Encroach Node=14156
       1  4886.3  5121.3
Encroach Node=14121.5
       1  4891.3  5116.3
Encroach Node=14083
       1  4896.3  5111.3
Encroach Node=13877.0
       1  4898.2  5086.9
Encroach Node=13580
       1 4896.35 5106.35
Encroach Node=12476
       1  4896.5  5106.5
Encroach Node=12164
       1 4928.69 5068.22
Encroach Node=12151
       1 4928.69 5068.22
Encroach Node=12138
       1 4938.69 5058.22
Encroach Node=11757
       1 4897.22 5092.98
Encroach Node=11096
       1 4928.83 5060.47
Encroach Node=10371
       1 4928.83  5071.3
Encroach Node=10050
       1 3744.05 3916.16
Encroach Node=9975
       13755.5353904.675
Encroach Node=9902
       13767.0233893.191
Encroach Node=9794
       1  4940.8  5047.7
Encroach Node=9694
       1  4940.8  5047.7
Encroach Node=9592
       1  4940.7  5047.7
Encroach Node=9569.5
       1  4940.7  5047.7
Encroach Node=9543
       1  4940.7  5047.7
Encroach Node=9418
       1  4940.8  5056.3
Encroach Node=9195
       1  4904.6  5094.6
Encroach Node=8997
       1 3511.88 3712.23
Encroach Node=8939
       1 3515.353676.402
Encroach Node=8856
       1 3518.82  3705.3
Encroach Node=8658
       1  4907.2  5077.2
Encroach Node=8307
       1 4926.13    5057
Encroach Node=7608
       1 4922.62 5072.09
Encroach Node=6350
       1 4901.94 5061.77
Encroach Node=5648
       1  4941.1    5070
Encroach Node=4948
       1  4931.3  5071.3
Encroach Node=4548
       1  4935.6  5062.5
Encroach Node=4493
       1  4935.6  5062.5
Encroach Node=4435
       1  4935.6  5062.5
Encroach Node=4329
       1  4929.4  5051.2
Encroach Node=3917
       1  4946.6  5051.2
Encroach Node=3579
       1    4945    5065
Encroach Node=3373
       1  4948.7  5067.9
Encroach Node=3353.5
       1  4948.7  5067.9
Encroach Node=3333
       1  4948.7  5067.9
Encroach Node=3233
       1  4940.1  5070.1
Encroach Node=2832
       1 4950.51    5058
Encroach Node=2658
       1 4933.91  5077.6
Encroach Node=2631
       1 4933.91  5077.6
Encroach Node=2604
       1 4933.91  5077.6
Encroach Node=2502
       1    4951  5046.1
Encroach Node=1628
       1    4951 5050.02
Encroach Node=922
       1  4946.4  5054.7
Encroach Node=243
       1  4946.4  5087.9
Encroach Node=133
       1  4927.5  5074.9
Encroach Node=122.5
       1  4927.5  5074.9
Encroach Node=111
       1  4928.8    5076
Encroach Reach=E117-00-00_0001
Encroach Node=36002
       1 4889.75    5080
Encroach Node=35901
       1 3464.54    3594
Encroach Node=35811
       1 3464.543563.323
Encroach Node=35718
       1 3464.543563.323
Encroach Node=35566.
       1  4958.1  5043.2
Encroach Node=35315
       1  4958.1    5076
Encroach Node=34437
       1  4849.4  5149.4
Encroach Node=34311
       1 4749.95 5249.95
Encroach Node=34267
       1 4749.95 5249.95
Encroach Node=34221
       1 4749.95 5249.95
Encroach Node=33907
       1 4751.15 5251.15
Encroach Node=33675
       1 4751.15 5251.15
Encroach Node=32920
       1 4750.65 5250.65
Encroach Node=32902
       1 4751.45 5251.45
Encroach Node=32836
       1 4748.52 5248.52
Encroach Node=32825.5
       1 4748.52 5248.52
Encroach Node=32811
       1 4748.52 5248.52
Encroach Node=32762
       1    4970    5040
Encroach Node=32747.5
       1    4970    5040
Encroach Node=32734
       1    4970    5040
Encroach Node=32700
       1    4970    5040
Encroach Node=32652
       1    4970    5040
Encroach Node=32602
       1    4970    5040
Encroach Node=32588
       1 4752.65 5252.65
Encroach Node=31272
       1 4752.65 5252.65
Encroach Node=29956
       1 4752.65 5252.65
Encroach Node=29929
       1 4752.65 5252.65
Encroach Node=29890.5
       1 4752.65 5252.65
Encroach Node=29852
       1 4752.65 5252.65
Encroach Node=29805
       1 3348.15 3712.31
Encroach Node=29680
       1 3348.15 3712.31
Encroach Node=29551
       1 3245.62  3641.6
Encroach Node=29500
       1 3228.96 3628.61
Encroach Node=29462
       1 3228.96 3628.61
Encroach Node=29416
       1 3228.96 3628.61
Encroach Node=29094
       1  4961.6    5140
Encroach Node=28999.5
       1  4961.6    5140
Encroach Node=28897
       1    4950    5037
Encroach Node=28684
       1    4970    5037
Encroach Node=28302
       1    4970    5037
Encroach Node=27886
       1    4875    5050
Encroach Node=27836
       1    4800    5200
Encroach Node=27778
       1    4935    5050
Encroach Node=27568
       1    4935    5035
Encroach Node=27267
       1    4750    5045
Encroach Node=25938
       1 4697.55 5297.55
Encroach Node=24962
       1  4834.6  5174.6
Encroach Node=24075
       1 4828.75 5168.75
Encroach Node=23347
       1 4818.75 5178.75
Encroach Node=22996
       1  4852.8  5152.8
Encroach Node=22931
       1  4921.9  5140.3
Encroach Node=22854
       1  4877.8  5127.8
Encroach Node=22615
       1 4865.45 5115.45
Encroach Node=22223
       1 4865.45 5115.45
Encroach Node=21280
       1 4895.15 5095.15
Encroach Node=20308
       1  4900.8  5100.8
Encroach Node=19566
       1    4915    5085
Encroach Node=19349
       1 4928.85 5078.85
Encroach Node=19322
       1  4925.2  5057.5
Encroach Node=19290
       1  4925.2  5057.5
Encroach Node=19077
       1    4952  5057.5
Encroach Node=18678
       1  4933.3  5055.7
Encroach Node=17828
       1  4926.5 5059.45
Encroach Node=17658
       1  4922.5  5057.7
Encroach Node=17630
       1  4922.5  5057.7
Encroach Node=17597
       1  4922.5  5060.1
Encroach Node=17414
       1    4920    5057
Encroach Node=16773
       1  4929.1  5079.1
Encroach Node=16140
       1  4903.6  5129.1
Encroach Node=15781
       13434.1113637.727
Encroach Node=15698
       13434.1113637.727
Encroach Node=15619
       13434.1113637.727
Encroach Node=15364
       1 4890.34  5122.4
Encroach Node=15001
       1  4874.7 5115.73
Encroach Node=14709
       1 3713.26 3953.26
Encroach Node=14698.5
       1 3714.51 3952.01
Encroach Node=14681
       1 3715.76 3950.76
Encroach Node=14156
       1  4886.3  5121.3
Encroach Node=14121.5
       1  4891.3  5116.3
Encroach Node=14083
       1  4896.3  5111.3
Encroach Node=13877.0
       1  4898.2  5086.9
Encroach Node=13580
       1 4896.35 5106.35
Encroach Node=12476
       1  4896.5  5106.5
Encroach Node=12164
       1 4928.69 5068.22
Encroach Node=12151
       1 4928.69 5068.22
Encroach Node=12138
       1 4938.69 5058.22
Encroach Node=11757
       1 4897.22 5092.98
Encroach Node=11096
       1 4928.83 5060.47
Encroach Node=10371
       1 4928.83  5071.3
Encroach Node=10050
       1 3744.05 3916.16
Encroach Node=9975
       13755.5353904.675
Encroach Node=9902
       13767.0233893.191
Encroach Node=9794
       1  4940.8  5047.7
Encroach Node=9694
       1  4940.8  5047.7
Encroach Node=9592
       1  4940.7  5047.7
Encroach Node=9569.5
       1  4940.7  5047.7
Encroach Node=9543
       1  4940.7  5047.7
Encroach Node=9418
       1  4940.8  5056.3
Encroach Node=9195
       1  4904.6  5094.6
Encroach Node=8997
       1 3511.88 3712.23
Encroach Node=8939
       1 3515.353676.402
Encroach Node=8856
       1 3518.82  3705.3
Encroach Node=8658
       1  4907.2  5077.2
Encroach Node=8307
       1 4926.13    5057
Encroach Node=7608
       1 4922.62 5072.09
Encroach Node=6350
       1 4901.94 5061.77
Encroach Node=5648
       1  4941.1    5070
Encroach Node=4948
       1  4931.3  5071.3
Encroach Node=4548
       1  4935.6  5062.5
Encroach Node=4493
       1  4935.6  5062.5
Encroach Node=4435
       1  4935.6  5062.5
Encroach Node=4329
       1  4929.4  5051.2
Encroach Node=3917
       1  4946.6  5051.2
Encroach Node=3579
       1    4945    5065
Encroach Node=3373
       1  4948.7  5067.9
Encroach Node=3353.5
       1  4948.7  5067.9
Encroach Node=3333
       1  4948.7  5067.9
Encroach Node=3233
       1  4940.1  5070.1
Encroach Node=2832
       1 4950.51    5058
Encroach Node=2658
       1 4933.91  5077.6
Encroach Node=2631
       1 4933.91  5077.6
Encroach Node=2604
       1 4933.91  5077.6
Encroach Node=2502
       1    4951  5046.1
Encroach Node=1628
       1    4951 5050.02
Encroach Node=922
       1  4946.4  5054.7
Encroach Node=243
       1  4946.4  5087.9
Encroach Node=133
       1  4927.5  5074.9
Encroach Node=122.5
       1  4927.5  5074.9
Encroach Node=111
       1  4928.8    5076
Computation Interval=1HOUR
Output Interval=1HOUR
Run HTab= 0
Run UNet= 0
Run PostProcess= 0
UNET Theta= 1
UNET ZTol= 0.02
UNET ZSATol= 0.1
UNET MxIter= 20
UNET MaxInSteps= 20
UNET DtIC= 0
UNET DtMin= 0
UNET MaxCRTS= 20
UNET WFStab= 2
UNET SFStab= 1
UNET WFX= 1
UNET SFX= 1
UNET Convert EG Bridges=-1
UNET Use Existing IB Tables=-1
Instantaneous Interval=1HOUR
Write IC File= 0
IC Time=0
Write Velocity= 0
Write Detailed= 0

--- E117-00-00.f01 (steady flow) ---

Flow Title=FEMA Effective June 2007
Version=Version 3.0.1  Mar 2001
Number of Profiles= 4
Profile Names=10PCT_10yr, 2PCT_50yr, 1PCT_100yr, 0.2PCT_500yr
River Rch & RM=E117-00-00,E117-00-00_0001       ,36002
     550     830     970    1500
River Rch & RM=E117-00-00,E117-00-00_0001       ,35315
     630     990    1150    1680
River Rch & RM=E117-00-00,E117-00-00_0001       ,34311
     690    1110    1280    1800
River Rch & RM=E117-00-00,E117-00-00_0001       ,33675
     770    1260    1460    1960
River Rch & RM=E117-00-00,E117-00-00_0001       ,32920
     790    1300    1500    2000
River Rch & RM=E117-00-00,E117-00-00_0001       ,32762
     800    1310    1510    2020
River Rch & RM=E117-00-00,E117-00-00_0001       ,32588
     840    1380    1580    2140
River Rch & RM=E117-00-00,E117-00-00_0001       ,29929
     910    1510    1720    2360
River Rch & RM=E117-00-00,E117-00-00_0001       ,29094
     960    1600    1800    2500
River Rch & RM=E117-00-00,E117-00-00_0001       ,27267
    1050    1750    2070    3610
River Rch & RM=E117-00-00,E117-00-00_0001       ,25938
    1120    1840    2190    3800
River Rch & RM=E117-00-00,E117-00-00_0001       ,24962
    1190    1930    2300    3970
River Rch & RM=E117-00-00,E117-00-00_0001       ,24075
    1280    2050    2450    4200
River Rch & RM=E117-00-00,E117-00-00_0001       ,22996
    1350    2140    2560    4360
River Rch & RM=E117-00-00,E117-00-00_0001       ,22223
    1440    2250    2710    4580
River Rch & RM=E117-00-00,E117-00-00_0001       ,21280
    1540    2380    2860    4810
River Rch & RM=E117-00-00,E117-00-00_0001       ,20308
    1642    2503    3025    5051
River Rch & RM=E117-00-00,E117-00-00_0001       ,19349
    1710    2600    3140    5150
River Rch & RM=E117-00-00,E117-00-00_0001       ,18678
    1790    2730    3280    5280
River Rch & RM=E117-00-00,E117-00-00_0001       ,17828
    1910    2900    3470    5450
River Rch & RM=E117-00-00,E117-00-00_0001       ,16773
    2020    3070    3660    5620
River Rch & RM=E117-00-00,E117-00-00_0001       ,15781
    2150    3270    3890    5800
River Rch & RM=E117-00-00,E117-00-00_0001       ,14709
    2300    3480    4120    6000
River Rch & RM=E117-00-00,E117-00-00_0001       ,13580
    2500    3770    4450    6260
River Rch & RM=E117-00-00,E117-00-00_0001       ,12164
    2660    4010    4710    6460
River Rch & RM=E117-00-00,E117-00-00_0001       ,11096
    2823    4253    4982    6660
River Rch & RM=E117-00-00,E117-00-00_0001       ,10050
    2960    4450    5220    6980
River Rch & RM=E117-00-00,E117-00-00_0001       ,8307
    3010    4530    5310    7110
River Rch & RM=E117-00-00,E117-00-00_0001       ,7608
    3110    4680    5490    7350
River Rch & RM=E117-00-00,E117-00-00_0001       ,6350
    3170    4770    5600    7490
River Rch & RM=E117-00-00,E117-00-00_0001       ,5648
    3320    4990    5860    7840
River Rch & RM=E117-00-00,E117-00-00_0001       ,3917
    3410    5130    6030    8070
River Rch & RM=E117-00-00,E117-00-00_0001       ,2832
    3520    5300    6220    8330
River Rch & RM=E117-00-00,E117-00-00_0001       ,1628
    3590    5400    6340    8490
River Rch & RM=E117-00-00,E117-00-00_0001       ,922
    3676    5527    6496    8698
Boundary for River Rch & Prof#=E117-00-00,E117-00-00_0001       , 1
Up Type= 0
Dn Type= 3
Dn Slope=.0012
Boundary for River Rch & Prof#=E117-00-00,E117-00-00_0001       , 2
Up Type= 0
Dn Type= 3
Dn Slope=.0012
Boundary for River Rch & Prof#=E117-00-00,E117-00-00_0001       , 3
Up Type= 0
Dn Type= 3
Dn Slope=.0012
Boundary for River Rch & Prof#=E117-00-00,E117-00-00_0001       , 4
Up Type= 0
Dn Type= 3
Dn Slope=.0012
DSS Import GetInterval= 0
DSS Import GetPeak= 0
DSS Import FillOption= 0

--- E117-00-00.f02 (steady flow) ---

Flow Title=Floodway
Version=Version 3.0.1  Mar 2001
Number of Profiles= 2
Profile Names=1PCT_100yr, 1PCTFloodway_100yrFW
River Rch & RM=E117-00-00,E117-00-00_0001       ,36002
     970     970
River Rch & RM=E117-00-00,E117-00-00_0001       ,35315
    1150    1150
River Rch & RM=E117-00-00,E117-00-00_0001       ,34311
    1280    1280
River Rch & RM=E117-00-00,E117-00-00_0001       ,33675
    1460    1460
River Rch & RM=E117-00-00,E117-00-00_0001       ,32920
    1500    1500
River Rch & RM=E117-00-00,E117-00-00_0001       ,32762
    1510    1510
River Rch & RM=E117-00-00,E117-00-00_0001       ,32588
    1580    1580
River Rch & RM=E117-00-00,E117-00-00_0001       ,29929
    1720    1720
River Rch & RM=E117-00-00,E117-00-00_0001       ,29094
    1800    1800
River Rch & RM=E117-00-00,E117-00-00_0001       ,27267
    2070    2070
River Rch & RM=E117-00-00,E117-00-00_0001       ,25938
    2190    2190
River Rch & RM=E117-00-00,E117-00-00_0001       ,24962
    2300    2300
River Rch & RM=E117-00-00,E117-00-00_0001       ,24075
    2450    2450
River Rch & RM=E117-00-00,E117-00-00_0001       ,22996
    2560    2560
River Rch & RM=E117-00-00,E117-00-00_0001       ,22223
    2710    2710
River Rch & RM=E117-00-00,E117-00-00_0001       ,21280
    2860    2860
River Rch & RM=E117-00-00,E117-00-00_0001       ,20308
    3025    3025
River Rch & RM=E117-00-00,E117-00-00_0001       ,19349
    3140    3140
River Rch & RM=E117-00-00,E117-00-00_0001       ,18678
    3280    3280
River Rch & RM=E117-00-00,E117-00-00_0001       ,17828
    3470    3470
River Rch & RM=E117-00-00,E117-00-00_0001       ,16773
    3660    3660
River Rch & RM=E117-00-00,E117-00-00_0001       ,15781
    3890    3890
River Rch & RM=E117-00-00,E117-00-00_0001       ,14709
    4120    4120
River Rch & RM=E117-00-00,E117-00-00_0001       ,13580
    4450    4450
River Rch & RM=E117-00-00,E117-00-00_0001       ,12164
    4710    4710
River Rch & RM=E117-00-00,E117-00-00_0001       ,11096
    4982    4982
River Rch & RM=E117-00-00,E117-00-00_0001       ,10050
    5220    5220
River Rch & RM=E117-00-00,E117-00-00_0001       ,8307
    5310    5310
River Rch & RM=E117-00-00,E117-00-00_0001       ,7608
    5490    5490
River Rch & RM=E117-00-00,E117-00-00_0001       ,6350
    5600    5600
River Rch & RM=E117-00-00,E117-00-00_0001       ,5648
    5860    5860
River Rch & RM=E117-00-00,E117-00-00_0001       ,3917
    6030    6030
River Rch & RM=E117-00-00,E117-00-00_0001       ,2832
    6220    6220
River Rch & RM=E117-00-00,E117-00-00_0001       ,1628
    6340    6340
River Rch & RM=E117-00-00,E117-00-00_0001       ,922
    6496    6496
Boundary for River Rch & Prof#=E117-00-00,E117-00-00_0001       , 1
Up Type= 0
Dn Type= 3
Dn Slope=.0012
Boundary for River Rch & Prof#=E117-00-00,E117-00-00_0001       , 2
Up Type= 0
Dn Type= 3
Dn Slope=.0012
DSS Import GetInterval= 0
DSS Import GetPeak= 0
DSS Import FillOption= 0

--- E117-00-00.g02 (geometry) ---

Geom Title=E117-00-00 June 2007
Program Version=3.13

River Reach=E117-00-00      ,E117-00-00_0001
Reach XY= 30
      3058931.56     13877161.89      3060197.31     13877459.29
      3060257.47     13877978.29      3062336.18     13879168.05
      3063490.03     13878870.63      3063905.83     13879265.59
      3065435.34     13879394.07       3066553.4     13879031.22
      3068629.79     13877609.34       3069315.5       13877415.
      3069727.01     13876963.51      3071167.98      13876645.8
      3071602.88     13875845.46       3071996.1     13875632.78
       3072490.9     13875710.91      3075355.48     13874802.05
      3075954.44      13874893.2      3076812.51     13874450.06
      3078051.23     13874505.61      3078995.67      13874870.2
      3080652.79     13874154.05      3081108.52     13874197.45
      3081440.12      13873728.7      3082974.84     13873348.49
       3084557.3     13872410.99      3086437.51      13872245.2
      3087191.85      13871810.3      3087954.87     13872114.99
      3089171.89     13872156.65        3090546.       13871730.

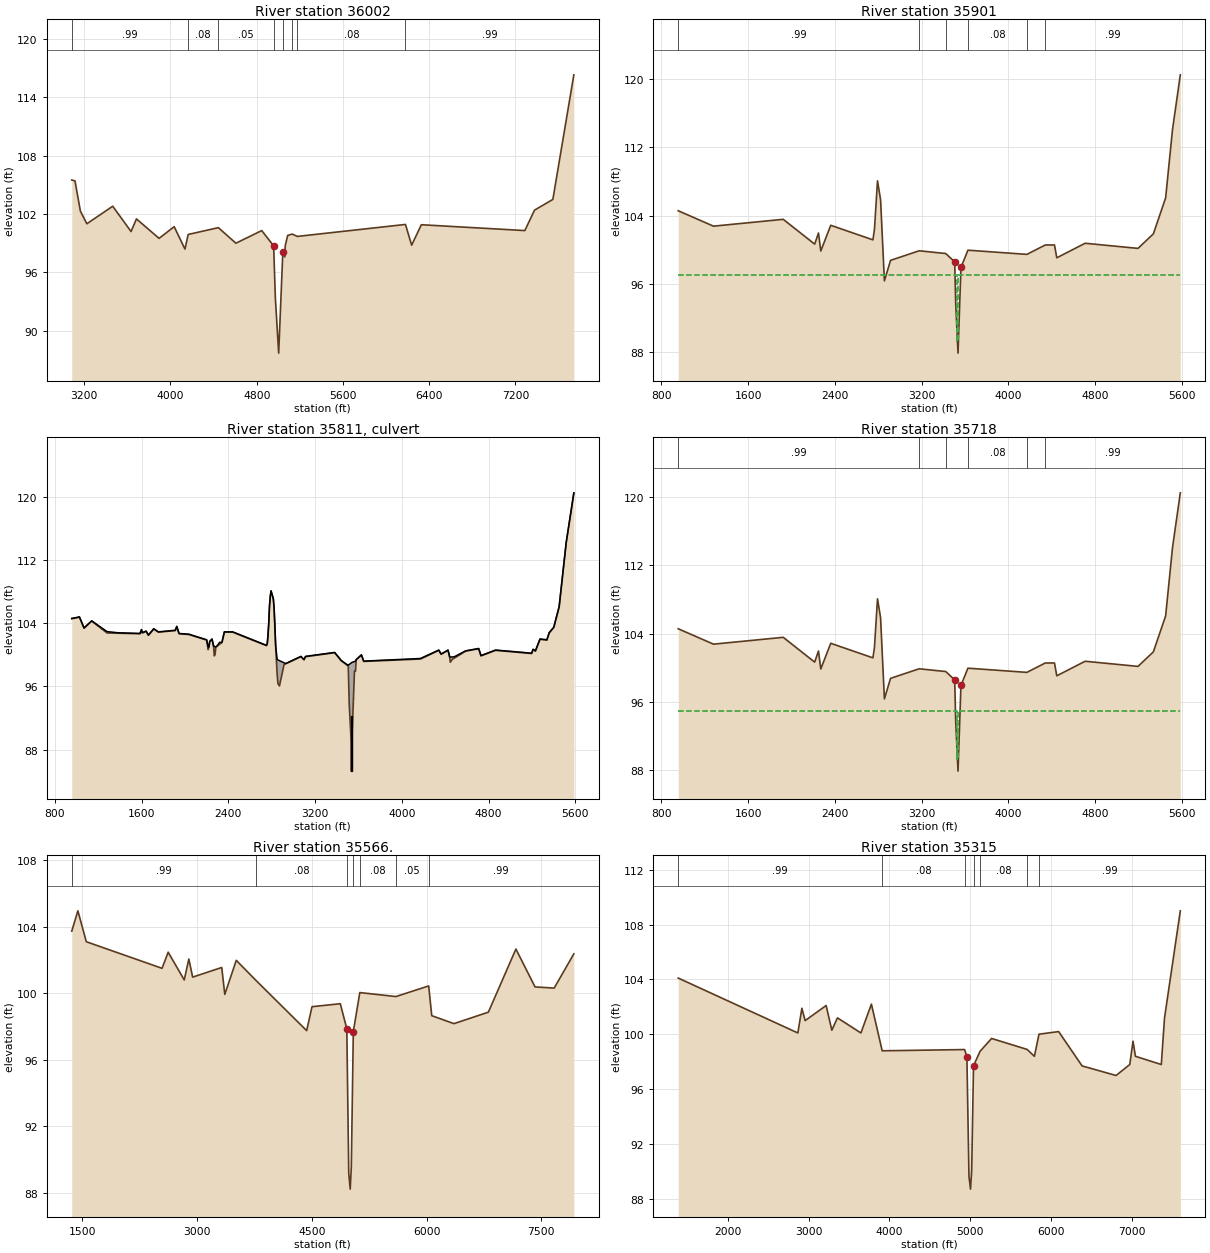
Type RM Length L Ch R = 1 ,36002   ,103.3,101,99.9
BEGIN DESCRIPTION:
Fisher - 4
Cross Section X27
Located At: US SP RR
END DESCRIPTION:
XS GIS Cut Line= 4
      3057464.66     13878380.25      3058629.92     13877530.15
      3058999.99     13877109.08       3059053.8     13874454.96
#Sta/Elev= 30
  3084.4   105.5  3114.4   105.4  3164.4   102.3  3224.4     101  3464.4   102.8
  3634.4   100.2  3684.4   101.5  3894.4    99.5  4034.4   100.7  4134.4    98.4
  4164.4    99.9  4444.4   100.6  4606.8      99  4846.8   100.3  4957.2   98.73
  4972.7   93.45  5003.9   87.71  5042.3   98.09  5060.6   97.59    5065   98.75
  5087.4    99.8  5129.7   99.94  5177.4    99.7    6180  100.93  6237.4    98.8
  6327.4   100.9  7287.4   100.3  7377.4   102.4  7547.4   103.5    7742   116.3
#Mann= 8 ,-1 , 0
  3084.4     .99       0  4164.4     .08       0  4444.4     .05       0
  4957.2     .04       0  5042.3     .04       0  5129.7     .05       0
  5177.4     .08       0    6180     .99       0
Bank Sta=4957.2,5042.3
Exp/Cntr=0.5,0.3

Type RM Length L Ch R = 1 ,35901   ,183.7,183,183.6
BEGIN DESCRIPTION:
Fisher - 3
END DESCRIPTION:
XS GIS Cut Line= 4
      3057757.66      13880658.6      3058964.78     13877308.46
      3059101.92     13877138.74      3059178.74     13874368.23
#Sta/Elev= 30
 955.018  104.571280.287  102.771923.755  103.572213.668  100.672249.024  101.97
2270.237   99.872362.161  102.87 2751.07  101.172765.212  102.372793.496  108.07
 2821.78  105.872857.136   96.372913.704   98.773177.738   99.893422.821   99.57
3505.765   98.593514.745    93.83536.241   87.923563.323   97.94 3627.67   99.96
4171.789   99.474341.636  100.574426.347  100.57 4447.56   99.074709.189  100.77
5197.092  100.175338.515  101.875451.652  106.075515.291  114.075587.133  120.47
#Mann= 6 ,-1 , 0
 955.018     .99       03177.738     .08       03422.821     .04       0
 3627.67     .08       04171.789     .05       04341.636     .99       0
#XS Ineff= 2 , 0
       0  3531.3      97  3540.3       0      97
Permanent Ineff=
       F       F
Bank Sta=3505.765,3563.323
Skew Angle= 45
Exp/Cntr=0.5,0.3

Type RM Length L Ch R = 2 ,35811   ,,,
BEGIN DESCRIPTION:
FISHER
Structure ID: E117-00-00-19
END DESCRIPTION:
Bridge Culvert--1,0,-1,-1, 0
Deck Dist Width WeirC Skew NumUp NumDn MinLoCord MaxHiCord MaxSubmerge Is_Ogee
10,160,2.6,45, 126, 126, , , 0.95, 0, ,,,
 955.018 955.867 955.938 991.2931025.7291026.6481068.1561138.8661280.2871380.202
1584.3441598.4861605.5571640.9121662.1251711.6231754.0491909.6131923.7551944.968
1960.0291995.3852009.527 2030.742036.8922087.3082199.5262213.668 2220.742221.659
2227.8112249.0242263.1662270.2372271.1562277.3082284.3792292.3692320.6542334.796
2340.9482348.9382362.161 2363.082439.9432462.0752645.923 2751.072758.1412765.212
2772.2832779.3542786.4252793.4962814.709 2821.782828.8512835.9222850.0652857.136
2871.2782899.1382913.7042928.7653029.2453069.2683097.5523111.6943177.7383380.395
3422.8213437.529 3440.573471.7533477.4093499.7533505.7653505.8353514.7453529.523
3536.2413538.6453541.4733563.323 3572.943574.4253579.0923608.1543627.315 3627.67
 3642.593648.5294171.7894341.4944341.6364362.7074426.3474440.488 4447.564468.772
4482.916 4588.984709.1894730.4034864.7525009.1455150.5665197.0925211.2355232.449
5274.8755291.9875299.058  5313.25338.5155355.6265359.7285398.0535402.1535426.336
5440.4795451.6525454.6225515.2915518.2615587.133
   104.6   104.6  104.61   104.7  104.81  104.78  103.41  104.31  102.94   102.8
  102.71  103.21  102.81  103.01  102.51  103.31  102.91  103.11  103.61  102.71
  102.69  102.66  102.64  102.62  102.61  102.39  101.91     101     101   101.1
  101.71  102.01  101.11   101.1   101.1  101.01  101.01  101.09   101.6  101.54
  101.61   102.1  102.91  102.91  102.91  102.79  101.78  101.21  101.41  102.41
  104.01  106.21  107.41  108.11  107.11  105.91  103.71  101.21    99.4   99.36
   99.27   99.09      99    98.9   99.55   99.81   99.41   99.81   99.93  100.31
   99.61   99.35    99.3   98.99   98.93   98.73   98.69   98.69   98.79   98.94
   99.01   99.04   99.05   99.16   99.21   99.22   99.41   99.77  100.01     100
   99.43   99.21   99.54  100.61  100.61  100.11  100.61   99.81   99.72   99.74
   99.75  100.51  100.81   99.91  100.61  100.44  100.27   100.2  100.71  100.51
  102.01  101.98  101.97  101.95  101.91  102.64  102.81  103.44  103.51  104.78
  105.52  106.11  106.48  114.11  114.37   120.5
                                                                                
                                                                                
                                                                                
                                                                                
                                                                                
                                                                                
                                                                                
                                                                                
                                                                                
                                                                                
                                                                                
                                                                                
                                                
 955.018 955.867 955.938 991.2931025.7291026.6481068.1561138.8661280.2871380.202
1584.3441598.4861605.5571640.9121662.1251711.6231754.0491909.6131923.7551944.968
1960.0291995.3852009.527 2030.742036.8922087.3082199.5262213.668 2220.742221.659
2227.8112249.0242263.1662270.2372271.1562277.3082284.3792292.3692320.6542334.796
2340.9482348.9382362.161 2363.082439.9432462.0752645.923 2751.072758.1412765.212
2772.2832779.3542786.4252793.4962814.709 2821.782828.8512835.9222850.0652857.136
2871.2782899.1382913.7042928.7653029.2453069.2683097.5523111.6943177.7383380.395
3422.8213437.529 3440.573471.7533477.4093499.7533505.7653505.8353514.7453529.523
3536.2413538.6453541.4733563.323 3572.943574.4253579.0923608.1543627.315 3627.67
 3642.593648.5294171.7894341.4944341.6364362.7074426.3474440.488 4447.564468.772
4482.916 4588.984709.1894730.4034864.7525009.1455150.5665197.0925211.2355232.449
5274.8755291.9875299.058  5313.25338.5155355.6265359.7285398.0535402.1535426.336
5440.4795451.6525454.6225515.2915518.2615587.133
   104.6   104.6  104.61   104.7  104.81  104.78  103.41  104.31  102.94   102.8
  102.71  103.21  102.81  103.01  102.51  103.31  102.91  103.11  103.61  102.71
  102.69  102.66  102.64  102.62  102.61  102.39  101.91     101     101   101.1
  101.71  102.01  101.11   101.1   101.1  101.01  101.01  101.09   101.6  101.54
  101.61   102.1  102.91  102.91  102.91  102.79  101.78  101.21  101.41  102.41
  104.01  106.21  107.41  108.11  107.11  105.91  103.71  101.21    99.4   99.36
   99.27   99.09      99    98.9   99.55   99.81   99.41   99.81   99.93  100.31
   99.61   99.35    99.3   98.99   98.93   98.73   98.69   98.69   98.79   98.94
   99.01   99.04   99.05   99.16   99.21   99.22   99.41   99.77  100.01     100
   99.43   99.21   99.54  100.61  100.61  100.11  100.61   99.81   99.72   99.74
   99.75  100.51  100.81   99.91  100.61  100.44  100.27   100.2  100.71  100.51
  102.01  101.98  101.97  101.95  101.91  102.64  102.81  103.44  103.51  104.78
  105.52  106.11  106.48  114.11  114.37   120.5
                                                                                
                                                                                
                                                                                
                                                                                
                                                                                
                                                                                
                                                                                
                                                                                
                                                                                
                                                                                
                                                                                
                                                                                
                                                
BR Coef= 1 , 1 , 0 ,1.25, 0 ,,,0.8,0,2,0,
WSPro=,,,, 1 ,,,, 0 ,,,, 0 ,,,,-1 ,-1 ,-1 , 0 , 0 , 0 , 0 , 0
Culvert=2,7,9,160,0.015,0.5,1,8,2,85.29,3535.8,85.29,3535.8,Culvert #1  , 0 ,10
Culvert Bottom n=0.015
BR U #Sta/Elev= 128
 955.018  104.57 955.867  104.57 955.938  104.57 991.293  104.671025.729  104.77
1026.648  104.741068.156  103.371138.866  104.271280.287  102.771380.202  102.74
1584.344  102.671598.486  103.171605.557  102.771640.912  102.971662.125  102.47
1711.623  103.271754.049  102.871909.613  103.071923.755  103.571944.968  102.67
1960.029  102.651995.385  102.622009.527   102.6 2030.74  102.582036.892  102.57
2087.308  102.352199.526  101.872213.668  100.67 2220.74  100.972221.659  101.06
2227.811  101.672249.024  101.972263.166  101.072270.237   99.872271.156    99.9
2277.308  100.072284.379  100.972292.369  101.052320.654  101.352334.796   101.5
2340.948  101.572348.938  102.062362.161  102.87 2363.08  102.872439.943  102.87
2462.075  102.752645.923  101.74 2751.07  101.172758.141  101.372765.212  102.37
2772.283  103.972779.354  106.172786.425  107.372793.496  108.072814.709  107.07
 2821.78  105.872828.851  103.672835.922  101.172850.065   97.472857.136   96.37
2871.278   96.072899.138   97.842913.704   98.772928.765   98.873029.245   99.51
3069.268   99.773097.552   99.373111.694   99.773177.738   99.893380.395  100.27
3422.821   99.573437.529   99.31 3440.57   99.263471.753   98.953477.409   98.89
3499.753   98.653505.765   98.593505.835   98.553514.745    93.83529.523   90.02
3532.635   89.033532.705    85.33539.069    85.3 3539.14      893541.473   89.91
3563.323   97.94 3572.94   97.943574.425   98.293579.092   99.373608.154   99.73
3627.315   99.97 3627.67   99.96 3642.59   99.393648.529   99.174171.789   99.47
4341.494  100.574341.636  100.574362.707  100.074426.347  100.574440.488   99.77
 4447.56   99.074468.772   99.474482.916   99.57 4588.98  100.474709.189  100.77
4730.403   99.874864.752  100.575009.145   100.45150.566  100.235197.092  100.17
5211.235  100.675232.449  100.475274.875  101.975291.987  101.945299.058  101.93
  5313.2  101.915338.515  101.875355.626   102.65359.728  102.775398.053   103.4
5402.153  103.475426.336  104.745440.479  105.485451.652  106.075454.622  106.44
5515.291  114.075518.261  114.335587.133  120.47
BR U #Mann= 6
 955.018     .993177.738     .083422.821     .043627.315     .084171.789     .05
4341.636     .99
BR D #Sta/Elev= 128
 955.018  104.57 955.867  104.57 955.938  104.57 991.293  104.671025.729  104.77
1026.648  104.741068.156  103.371138.866  104.271280.287  102.771380.202  102.74
1584.344  102.671598.486  103.171605.557  102.771640.912  102.971662.125  102.47
1711.623  103.271754.049  102.871909.613  103.071923.755  103.571944.968  102.67
1960.029  102.651995.385  102.622009.527   102.6 2030.74  102.582036.892  102.57
2087.308  102.352199.526  101.872213.668  100.67 2220.74  100.972221.659  101.06
2227.811  101.672249.024  101.972263.166  101.072270.237   99.872271.156    99.9
2277.308  100.072284.379  100.972292.369  101.052320.654  101.352334.796   101.5
2340.948  101.572348.938  102.062362.161  102.87 2363.08  102.872439.943  102.87
2462.075  102.752645.923  101.74 2751.07  101.172758.141  101.372765.212  102.37
2772.283  103.972779.354  106.172786.425  107.372793.496  108.072814.709  107.07
 2821.78  105.872828.851  103.672835.922  101.172850.065   97.472857.136   96.37
2871.278   96.072899.138   97.842913.704   98.772928.765   98.873029.245   99.51
3069.268   99.773097.552   99.373111.694   99.773177.738   99.893380.395  100.27
3422.821   99.573437.529   99.31 3440.57   99.263471.753   98.953477.409   98.89
3499.753   98.653505.765   98.593505.835   98.553514.745    93.83529.523   90.02
3532.635   89.033532.705    85.33539.069    85.3 3539.14      893541.473   89.91
3563.323   97.94 3572.94   97.943574.425   98.293579.092   99.373608.154   99.73
3627.315   99.97 3627.67   99.96 3642.59   99.393648.529   99.174171.789   99.47
4341.494  100.574341.636  100.574362.707  100.074426.347  100.574440.488   99.77
 4447.56   99.074468.772   99.474482.916   99.57 4588.98  100.474709.189  100.77
4730.403   99.874864.752  100.575009.145   100.45150.566  100.235197.092  100.17
5211.235  100.675232.449  100.475274.875  101.975291.987  101.945299.058  101.93
  5313.2  101.915338.515  101.875355.626   102.65359.728  102.775398.053   103.4
5402.153  103.475426.336  104.745440.479  105.485451.652  106.075454.622  106.44
5515.291  114.075518.261  114.335587.133  120.47
BR D #Mann= 6
 955.018     .993177.738     .083422.821     .043627.315     .084171.789     .05
4341.636     .99
BC Design=,, 0 ,, 0 ,,,,,,
BC HTab HWMax=120.47

Type RM Length L Ch R = 1 ,35718   ,165.1,152,136.8
BEGIN DESCRIPTION:
Fisher - 2
END DESCRIPTION:
XS GIS Cut Line= 4
      3057921.91      13880739.7      3059128.75     13877390.35
      3059266.41     13877219.97      3059343.28     13874447.77
#Sta/Elev= 30
 955.018  104.571280.287  102.771923.755  103.572213.668  100.672249.024  101.97
2270.237   99.872362.161  102.87 2751.07  101.172765.212  102.372793.496  108.07
 2821.78  105.872857.136   96.372913.704   98.773177.738   99.893422.821   99.57
3505.765   98.593514.745    93.83536.241   87.923563.323   97.94 3627.67   99.96
4171.789   99.474341.636  100.574426.347  100.57 4447.56   99.074709.189  100.77
5197.092  100.175338.515  101.875451.652  106.075515.291  114.075587.133  120.47
#Mann= 6 ,-1 , 0
 955.018     .99       03177.738     .08       03422.821     .04       0
 3627.67     .08       04171.789     .05       04341.636     .99       0
#XS Ineff= 2 , 0
       0  3531.3      95  3540.3       0      95
Permanent Ineff=
       F       F
Bank Sta=3505.765,3563.323
Skew Angle= 45
Exp/Cntr=0.5,0.3

Type RM Length L Ch R = 1 ,35566.  ,262.2,251,237.6
BEGIN DESCRIPTION:
Fisher - 1
Interpolated channel; LIDAR overbanks
END DESCRIPTION:
XS GIS Cut Line= 4
        3058090.       13880788.      3059271.34     13877536.21
      3059365.43     13877256.53      3059443.24     13874450.54
#Sta/Elev= 30
  1363.5  103.75  1443.5  104.97  1553.5  103.11  2543.5  101.51  2623.5  102.48
  2833.5  100.81  2893.5  102.07  2943.5  100.98  3323.5  101.56  3363.5   99.94
  3513.5  101.99  3773.5  100.77  4433.5   97.76  4503.5    99.2  4873.2   99.38
  4958.1   97.87  4983.7   89.15  5002.8   88.22  5017.2   89.57  5043.2    97.7
  5128.3  100.05    5600   99.81  6028.3  100.45  6068.3   98.66  6358.3   98.18
  6808.3   98.87  7168.3  102.67  7418.3  100.39  7668.3  100.32  7925.4  102.38
#Mann= 7 ,-1 , 0
  1363.5     .99       0  3773.5     .08       0  4958.1     .04       0
  5043.2     .04       0  5128.3     .08       0    5600     .05       0
  6028.3     .99       0
Bank Sta=4958.1,5043.2
Exp/Cntr=0.3,0.1

Type RM Length L Ch R = 1 ,35315   ,841.3,878,910.2
BEGIN DESCRIPTION:
Cross Section X26
Located At: US SOMMERMEYER
END DESCRIPTION:
XS GIS Cut Line= 4
      3058263.38     13880760.17       3059568.6     13877633.92
      3059580.05     13877145.12      3061141.42     13875408.63
#Sta/Elev= 30
  1386.5   104.1  2866.6   100.1  2916.6   101.9  2956.6     101  3216.6   102.1
  3286.6   100.3  3356.6   101.2  3646.6   100.1  3776.6   102.2    3910    98.8
  4929.4   98.89  4958.1   98.37  4983.7   89.65  5002.8   88.72  5017.2   90.07
    5040   97.71  5120.8   98.76  5263.3    99.7  5703.3    98.9  5793.3    98.4
    5850  100.01  6093.3   100.2  6383.3    97.7  6803.3      97  6973.3    97.8
  7013.3    99.5  7043.3    98.4  7363.3    97.8  7403.3   101.2  7598.5     109
#Mann= 7 ,-1 , 0
  1386.5     .99       0    3910     .08       0  4929.4     .04       0
    5040     .04       0  5120.8     .08       0  5703.3     .05       0
    5850     .99       0
Bank Sta=4958.1,5040
Exp/Cntr=0.3,0.1

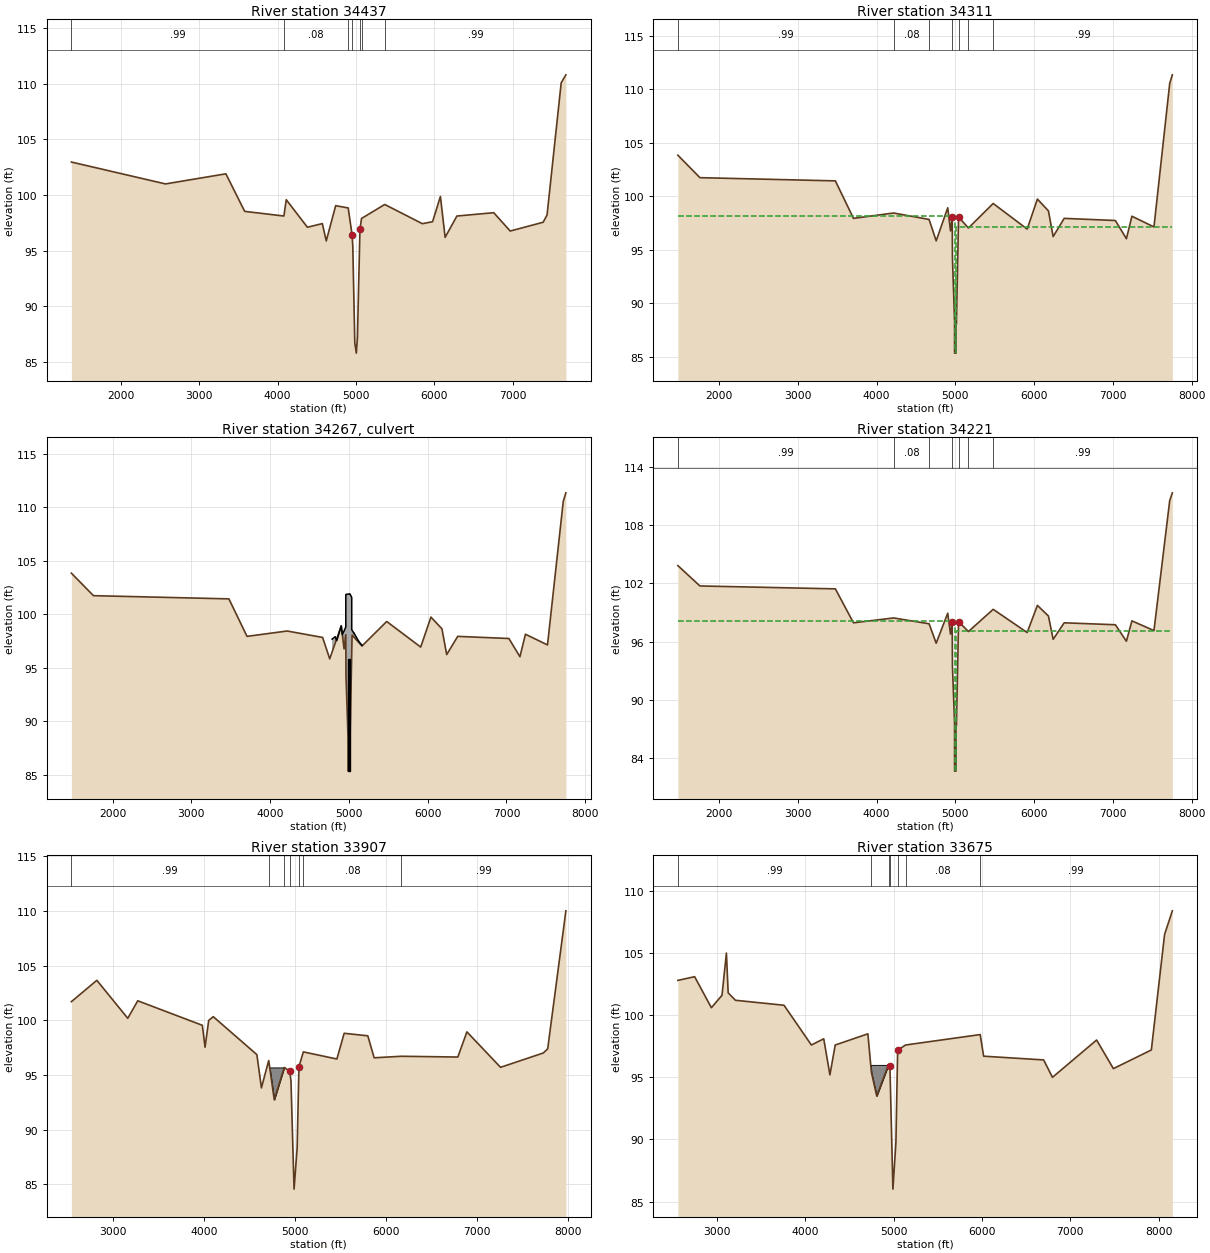
Type RM Length L Ch R = 1 ,34437   ,133.3,126,117.5
BEGIN DESCRIPTION:
Sommermeyer - 4
Interpolated channel, LIDAR overbanks
END DESCRIPTION:
XS GIS Cut Line= 4
       3058484.5       13880792.      3060048.27      13877717.3
      3060342.81     13877685.95       3061453.4     13875379.58
#Sta/Elev= 30
  1369.7  102.97  2569.7     101  3339.7  101.91  3579.7   98.53  4079.7   98.11
  4109.7   99.58  4379.7    97.1  4569.7   97.43  4619.7   95.87  4739.7   99.04
  4899.4   98.84  4949.4    96.4  4958.1   95.42  4983.7    86.7  5002.8   85.77
  5017.2   87.12  5049.4   96.91  5069.4   97.89  5365.6   99.15  5845.6   97.42
  5975.6    97.6  6075.6   99.87  6135.6   96.19  6285.6   98.11  6755.6   98.41
  6965.6   96.76  7385.6   97.55  7435.6   98.21  7615.6   110.1  7675.5  110.82
#Mann= 7 ,-1 , 0
  1369.7     .99       0  4079.7     .08       0  4899.4     .04       0
  4949.4     .03       0  5049.4     .04       0  5069.4     .08       0
  5365.6     .99       0
Bank Sta=4949.4,5049.4
Exp/Cntr=0.5,0.3

Type RM Length L Ch R = 1 ,34311   ,88.7,90,90.6
BEGIN DESCRIPTION:
Sommermeyer - 3
END DESCRIPTION:
XS GIS Cut Line= 4
      3058532.17     13880847.98      3060040.05     13877881.93
      3060372.47     13877778.97      3061501.96     13875433.35
#Sta/Elev= 30
  1476.2  103.83  1756.2  101.73  3476.2  101.43  3706.2   97.93    4216   98.43
  4666.2   97.83  4756.2   95.83  4902.8   98.92  4938.4   96.76  4960.1   98.08
  4962.8   94.23 4989.54    88.4 4989.55   85.35 5007.45   85.35 5007.46   88.13
  5013.1   88.05  5040.3   98.05  5165.9   97.03    5480   99.32  5911.5   96.93
  6041.5   99.73  6181.5   98.63  6241.5   96.23  6381.5   97.93  7031.5   97.73
  7171.5   96.03  7241.5   98.13  7521.5   97.13  7721.5  110.53  7754.9  111.33
#Mann= 7 ,-1 , 0
  1476.2     .99       0    4216     .08       0  4666.2     .04       0
  4960.1     .03       0  5040.3     .04       0  5165.9     .08       0
    5480     .99       0
#XS Ineff= 2 , 0
       0 4989.56   98.13 5007.45       0   97.08
Permanent Ineff=
       F       F
Bank Sta=4960.1,5040.3
Exp/Cntr=0.5,0.3

Type RM Length L Ch R = 2 ,34267   ,,,
BEGIN DESCRIPTION:
SOMMERMEYER; Half of culvert filled with debris
Structure ID: E117-00-00-18
END DESCRIPTION:
Bridge Culvert--1,0,-1,-1, 0
Deck Dist Width WeirC Skew NumUp NumDn MinLoCord MaxHiCord MaxSubmerge Is_Ogee
10,68,2.6,0, 32, 32, , , 0.95, 0, ,,,
  4786.2  4825.6  4845.6  4858.7  4868.3  4902.8    4916  4938.4  4959.6  4960.1
 4960.29  4960.4 4960.51  4962.8  4968.8  4980.4  4985.8  5012.5  5013.1  5019.5
  5019.6 5035.79  5035.9 5036.01  5040.3    5064  5065.7  5069.2  5112.5    5135
  5151.5  5165.9
   97.67    97.9   97.53   97.84   98.07    98.9    98.1   98.43    98.8   98.81
   98.81  101.81  101.81  101.85  101.86  101.87  101.87   101.9  101.89   101.8
   101.8  101.56  101.56   98.56    98.5   98.22   98.23   98.18   97.62   97.37
   97.22    97.1
                                                                                
                                                                                
                                                                                
                
  4786.2  4825.6  4845.6  4858.7  4868.3  4902.8    4916  4938.4  4959.6  4960.1
 4960.29  4960.4 4960.51  4962.8  4968.8  4980.4  4985.8  5012.5  5013.1  5019.5
  5019.6 5035.79  5035.9 5036.01  5040.3    5064  5065.7  5069.2  5112.5    5135
  5151.5  5165.9
   97.67    97.9   97.53   97.84   98.07    98.9    98.1   98.43    98.8   98.81
   98.81  101.81  101.81  101.85  101.86  101.87  101.87   101.9  101.89   101.8
   101.8  101.56  101.56   98.56    98.5   98.22   98.23   98.18   97.62   97.37
   97.22    97.1
                                                                                
                                                                                
                                                                                
                
BR Coef= 1 , 1 , 0 ,1.25, 0 ,,,0.8,0,2,0,
WSPro=,,,, 1 ,,,, 0 ,,,, 0 ,,,,-1 ,-1 ,-1 , 0 , 0 , 0 , 0 , 0
Culvert=2,10.5,8.5,68,0.015,0.5,1,8,2,85.36,4993.8,82.64,4993.8,Culvert #1  , 0 ,10
Culvert Bottom n=0.015
Culvert=2,10.5,8.5,68,0.015,0.5,1,8,2,85.35,5003.2,82.64,5003.2,Culvert #2  , 0 ,10
Culvert Bottom n=0.015
BC Design=,, 0 ,, 0 ,,,,,,
BC HTab HWMax=111.33

Type RM Length L Ch R = 1 ,34221   ,362.3,314,294.1
BEGIN DESCRIPTION:
Sommermeyer - 2
END DESCRIPTION:
XS GIS Cut Line= 4
      3058532.95     13880935.53      3060039.88     13877971.37
      3060372.35     13877868.39  3061500.18687513875526.2158987
#Sta/Elev= 30
  1476.2  103.83  1756.2  101.73  3476.2  101.43  3706.2   97.93    4216   98.43
  4666.2   97.83  4756.2   95.83  4902.8   98.92  4938.4   96.76  4959.6   97.98
  4962.8   93.47 4989.54   87.64 4989.55   82.64 5007.45   82.64 5007.46   87.37
  5013.1   87.29  5040.3   98.05  5165.9   97.03    5480   99.32  5911.5   96.93
  6041.5   99.73  6181.5   98.63  6241.5   96.23  6381.5   97.93  7031.5   97.73
  7171.5   96.03  7241.5   98.13  7521.5   97.13  7721.5  110.53  7754.9  111.33
#Mann= 7 ,-1 , 0
  1476.2     .99       0    4216     .08       0  4666.2     .04       0
  4959.6     .03       0  5040.3     .04       0  5165.9     .08       0
    5480     .99       0
#XS Ineff= 2 , 0
       0 4989.56   98.13 5007.45       0   97.08
Permanent Ineff=
       F       F
Bank Sta=4959.6,5040.3
Exp/Cntr=0.5,0.3

Type RM Length L Ch R = 1 ,33907   ,236,232,231.8
BEGIN DESCRIPTION:
Sommermeyer - 1
Interpolated channel, LIDAR overbanks
END DESCRIPTION:
XS GIS Cut Line= 5
       3059154.1      13880192.1      3060316.34     13878334.56
      3060582.45     13877912.67      3061680.38     13875612.98
  3061766.548332  13875432.49449
#Sta/Elev= 30
  2542.4   101.7  2822.4  103.65  3162.4  100.18  3272.4  101.78  3982.4   99.54
  4012.4   97.54  4052.4   99.98  4102.4  100.33  4582.4   96.86  4632.4   93.82
  4712.4   96.32  4773.6   92.74  4883.6   95.69  4943.6   95.35  4957.4   94.45
  4991.3   84.57  5025.3   88.35  5044.9   95.75  5093.6   97.11  5462.4   96.46
  5542.4   98.81  5802.4   98.58  5872.4   96.57  6172.4   96.71  6792.4   96.64
  6892.4   98.94  7262.4    95.7  7732.4   97.01  7780.8   97.39  7980.8     110
#Mann= 7 ,-1 , 0
  2542.4     .99       0  4712.4    .025       0  4883.6     .04       0
  4943.6     .03       0  5044.9     .04       0  5093.6     .08       0
  6172.4     .99       0
#Block Obstruct= 1 ,-1
    4700  4883.6   95.69
Bank Sta=4943.6,5044.9
Exp/Cntr=0.3,0.1

Type RM Length L Ch R = 1 ,33675   ,741.6,755,813.3
BEGIN DESCRIPTION:
Cross Section XS 25
Detention pond on left overbank
END DESCRIPTION:
XS GIS Cut Line= 4
      3059197.01     13880212.96      3059661.45     13879754.57
      3060836.36     13877952.74      3062016.32     13875415.83
#Sta/Elev= 30
  2555.1   102.8  2745.1   103.1  2935.1   100.6  3055.1   101.6  3105.1     105
  3125.1   101.8  3207.7   101.2  3757.7   100.8  4067.7    97.6  4207.7    98.1
  4277.7    95.2  4337.7    97.6  4707.7    98.5  4747.7    95.4  4807.7    93.5
  4942.5   96.03  4957.4   95.88  4991.3      86  5025.3   89.78  5044.9   97.18
  5134.3    97.6    5980   98.44  6018.7    96.7  6698.7    96.4  6798.7      95
  7298.7      98  7488.7    95.7  7918.7    97.2  8068.7   106.5  8156.6   108.4
#Mann= 7 ,-1 , 0
  2555.1     .99       0  4747.7    .026       0  4942.5     .04       0
  4957.4     .03       0  5044.9     .04       0  5134.3     .08       0
    5980     .99       0
#Block Obstruct= 1 ,-1
 4743.45 4941.95      96
Bank Sta=4957.4,5044.9
Exp/Cntr=0.3,0.1