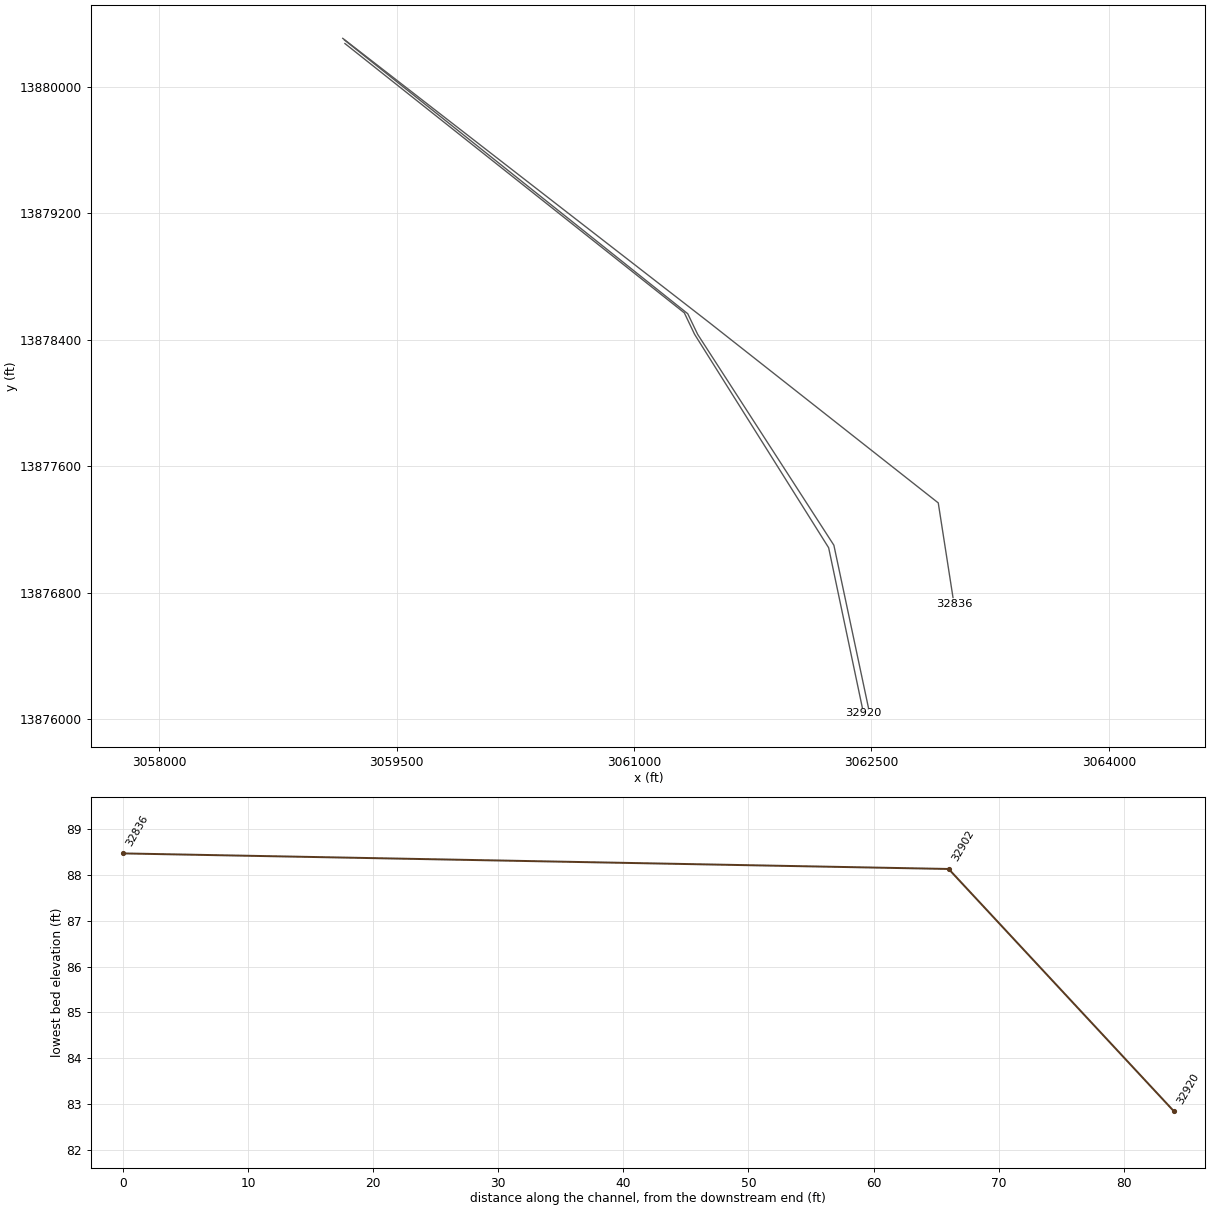
HEC-RAS study E117-00-00.prj: E117-00-00

--- E117-00-00.g02 (geometry) --- (continued)

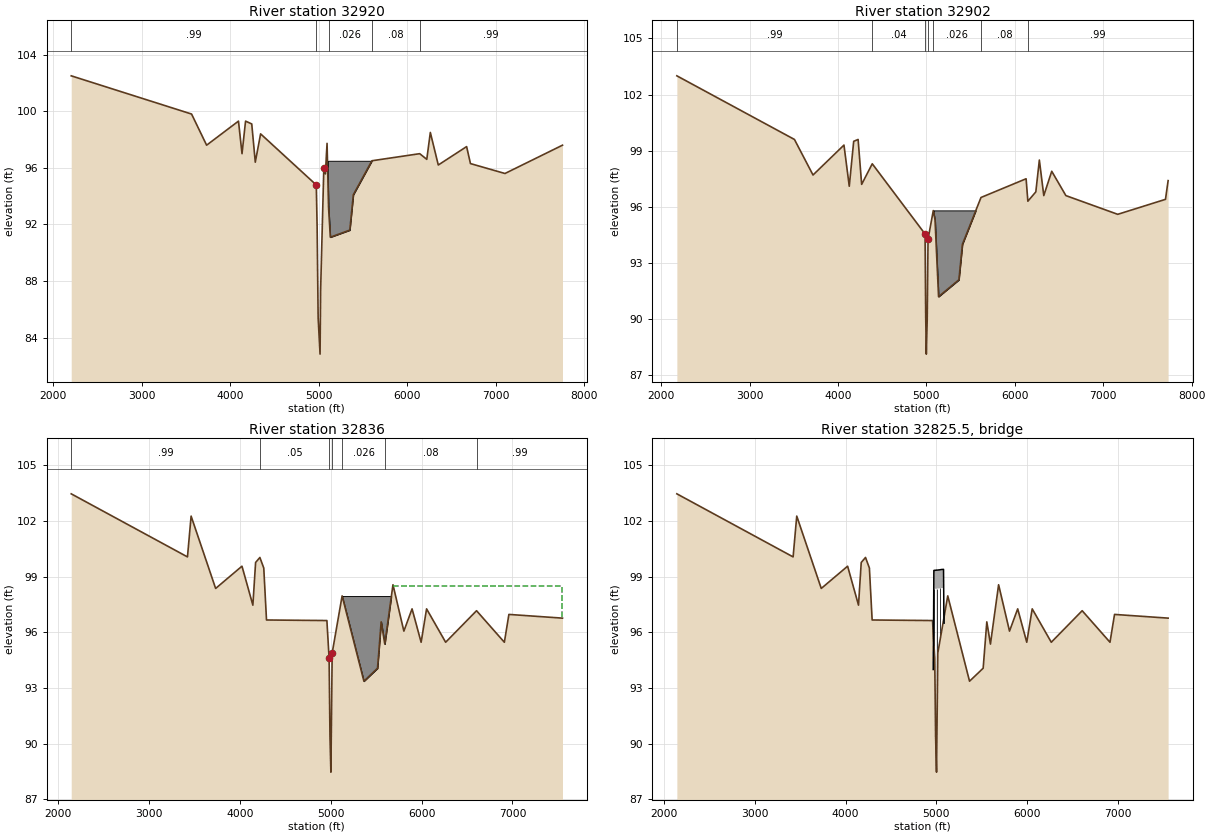
Type RM Length L Ch R = 1 ,32920   ,9.8,18,17.9
BEGIN DESCRIPTION:
Cross Section E117-00-00-X24B
Right overbank spills to road ditch that eventually spills to E115-04 as well as an unstudied ditch that flows into E117-00-00
END DESCRIPTION:
XS GIS Cut Line= 5
      3059174.09       13880272.       3061318.5     13878569.49
      3061383.11      13878434.2      3062230.34     13877084.49
 3062450.771021113876037.4443787
#Sta/Elev= 30
  2201.3   102.5  3561.3    99.8  3731.3    97.6  4091.3    99.3  4131.3      97
  4171.3    99.3  4241.3    99.1  4281.3    96.4  4341.3    98.4  4970.6   94.79
    4980   91.84  4991.6   85.41  5013.3   82.84  5019.6   87.37  5055.8      96
  5073.3   95.57  5092.3   97.73  5109.3    93.2  5129.3    91.1  5349.3    91.6
  5389.3    94.1  5599.3    96.5  6139.3      97  6219.3    96.6  6259.3    98.5
  6349.3    96.2  6669.3    97.5  6712.9    96.3  7102.9    95.6  7752.9    97.6
#Mann= 5 ,-1 , 0
  2201.3     .99       0  4970.6     .04       0  5109.3    .026       0
  5599.3     .08       0  6139.3     .99       0
#Block Obstruct= 1 ,-1
    5103    5599    96.5
Bank Sta=4970.6,5055.8
Exp/Cntr=0.3,0.1

Type RM Length L Ch R = 1 ,32902   ,39.6,66,153.8
BEGIN DESCRIPTION:
PL1_E117-00-00-PL17B - 4
Cross Section E117-00-00-XS24A-INTERP
Right overbank spills to road ditch that eventually spills to E115-04 as well as an unstudied ditch that flows into E117-00-00
END DESCRIPTION:
XS GIS Cut Line= 6
      3059170.97     13880294.66      3061340.06     13878564.02
      3061376.99     13878487.16      3061402.94     13878433.26
      3062263.41     13877100.48 3062481.692491713876073.4043967
#Sta/Elev= 30
  2177.4     103  3507.4    99.6  3717.4    97.7  4067.4    99.3  4127.4    97.1
  4177.4    99.5  4227.4    99.6  4267.4    97.2  4387.4    98.3  4984.5   94.55
    4992   90.11  4998.8   88.13  5008.9   89.96  5018.4   94.27  5077.6    95.8
  5097.4    95.3  5137.4    91.2  5367.4    92.1  5407.4      94  5617.4    96.5
  6127.4    97.5  6147.4    96.3  6237.4    96.8  6277.4    98.5  6327.4    96.6
  6417.4    97.9  6577.4    96.6  7163.8    95.6  7703.8    96.4  7733.8    97.4
#Mann= 7 ,-1 , 0
  2177.4     .99       0  4387.4     .04       0  4984.5     .04       0
  5018.4     .04       0  5077.6    .026       0  5617.4     .08       0
  6147.4     .99       0
#Block Obstruct= 1 ,-1
 5076.42 5654.18   95.81
Bank Sta=4984.5,5018.4
Exp/Cntr=0.5,0.3

Type RM Length L Ch R = 1 ,32836   ,22.8,25,24
BEGIN DESCRIPTION:
PL1_E117-00-00-PL17B - 3
Right overbank spills to road ditch that eventually spills to E115-04 as well as an unstudied ditch that flows into E117-00-00
END DESCRIPTION:
XS GIS Cut Line= 5
      3059160.37      13880304.9      3061385.35     13878578.57
      3061477.35      13878507.1      3062922.89     13877368.04
 3063022.093955613876730.7299335
#Sta/Elev= 30
  2142.2  103.47  3422.2  100.07  3462.2  102.27  3732.2   98.37  4022.3   99.57
  4142.2   97.47  4172.2   99.77  4219.4  100.04  4262.2   99.47  4292.3   96.67
 4957.17   96.64 4981.57   94.61 4991.07   90.41 5001.17   88.47 5015.47   94.89
  5124.9   97.97  5364.8   93.37  5514.8   94.07  5554.9   96.57  5594.9   95.37
  5684.8   98.57  5804.8   96.07  5894.9   97.27  5994.8   95.47  6054.8   97.27
  6264.8   95.47  6604.9   97.17  6911.2   95.47  6961.2   96.97  7551.3   96.77
#Mann= 7 ,-1 , 0
  2142.2     .99       0  4219.4     .05       0 4981.57     .04       0
 5015.47     .05       0  5124.9    .026       0  5594.9     .08       0
  6604.9     .99       0
#XS Ineff= 3 ,-1
    4500 4971.83   95.38 5081.32 5687.94   96.54 5687.94  7551.2   98.48
Permanent Ineff=
       F       F       F
#Block Obstruct= 1 ,-1
 5126.94    5665   97.96
Bank Sta=4981.57,5015.47
Exp/Cntr=0.5,0.3

Type RM Length L Ch R = 3 ,32825.5 ,,,
BEGIN DESCRIPTION:
PL1_E117-00-00-PL17B
END DESCRIPTION:
Bridge Culvert--1,0,-1,-1, 0
Deck Dist Width WeirC Skew NumUp NumDn MinLoCord MaxHiCord MaxSubmerge Is_Ogee
10,1,2.6,0, 24, 24, , , 0.95, 0, ,,,
    4965 4968.33 4968.44 4968.53 4971.83 4981.57 4991.07 4996.07 4996.97 4999.07
 5001.17 5002.97 5003.77 5007.97 5015.47 5026.27 5031.27 5053.77 5078.43 5081.32
 5081.43 5081.53  5084.8  5084.9
      94   96.38   96.47   96.55   99.34   99.35   99.35   99.35   99.35   99.36
   99.36   99.36   99.36   99.36   99.36   99.37   99.37   99.39    99.4   97.64
   97.57   97.54   96.53    96.5
    93.9   95.44   95.43   95.55   98.34   98.35   98.35   98.35   98.35   98.36
   98.36   98.36   98.36   98.36   98.36   98.37   98.37   98.39    98.4   96.64
   96.32   96.32    96.5    96.5
    4965 4968.33 4968.44 4968.53 4971.83 4981.57 4991.07 4996.07 4996.97 4999.07
 5001.17 5002.97 5003.77 5007.97 5015.47 5026.27 5031.27 5053.77 5078.43 5081.32
 5081.43 5081.53  5084.8  5084.9
      94   96.38   96.47   96.55   99.34   99.35   99.35   99.35   99.35   99.36
   99.36   99.36   99.36   99.36   99.36   99.37   99.37   99.39    99.4   97.64
   97.57   97.54   96.53    96.5
    93.9   95.44   95.43   95.55   98.34   98.35   98.35   98.35   98.35   98.36
   98.36   98.36   98.36   98.36   98.36   98.37   98.37   98.39    98.4   96.64
   96.32   96.32    96.5    96.5
Pier Skew, UpSta & Num, DnSta & Num=  ,4973.7, 2 ,4973.7, 2 , 0 , 0 , 0 ,,
     1.3     1.3
   99.58  104.57
     1.3     1.3
   99.58  104.57
Pier Skew, UpSta & Num, DnSta & Num=  ,5008.9, 2 ,5008.9, 2 , 0 , 0 , 0 ,,
     1.1     1.1
   94.34  104.59
     1.1     1.1
   94.34  104.59
Pier Skew, UpSta & Num, DnSta & Num=  ,5042.8, 2 ,5042.8, 2 , 0 , 0 , 0 ,,
     1.3     1.3
   99.82  104.61
     1.3     1.3
   99.82  104.61
Pier Skew, UpSta & Num, DnSta & Num=  ,5076.8, 2 ,5076.8, 2 , 0 , 0 , 0 ,,
     1.3     1.3
  100.13  104.63
     1.3     1.3
  100.13  104.63
BR Coef= 1 , 1 , 0 ,1.25, 0 ,,,0.8,-1,2,0,
WSPro=,,,, 1 ,,,, 0 ,,,, 0 ,,,,-1 ,-1 ,-1 , 0 , 0 , 0 , 0 , 0
BC Design=,, 0 ,, 0 ,,,,,,
BC HTab HWMax=103.43