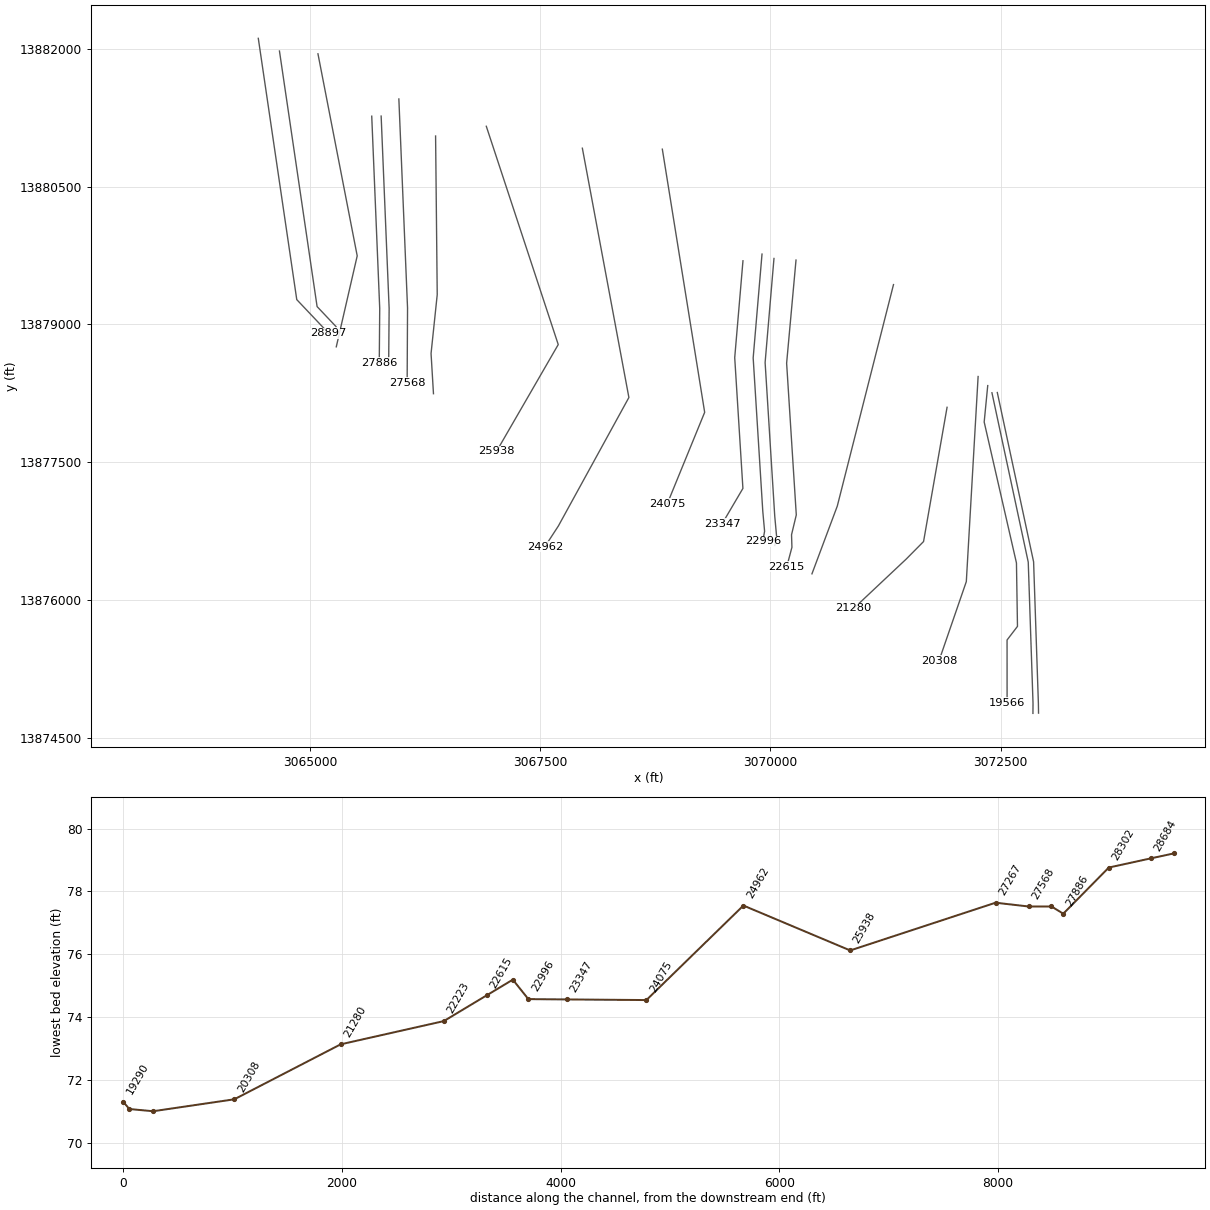
HEC-RAS study E117-00-00.prj: E117-00-00

--- E117-00-00.g02 (geometry) --- (continued)

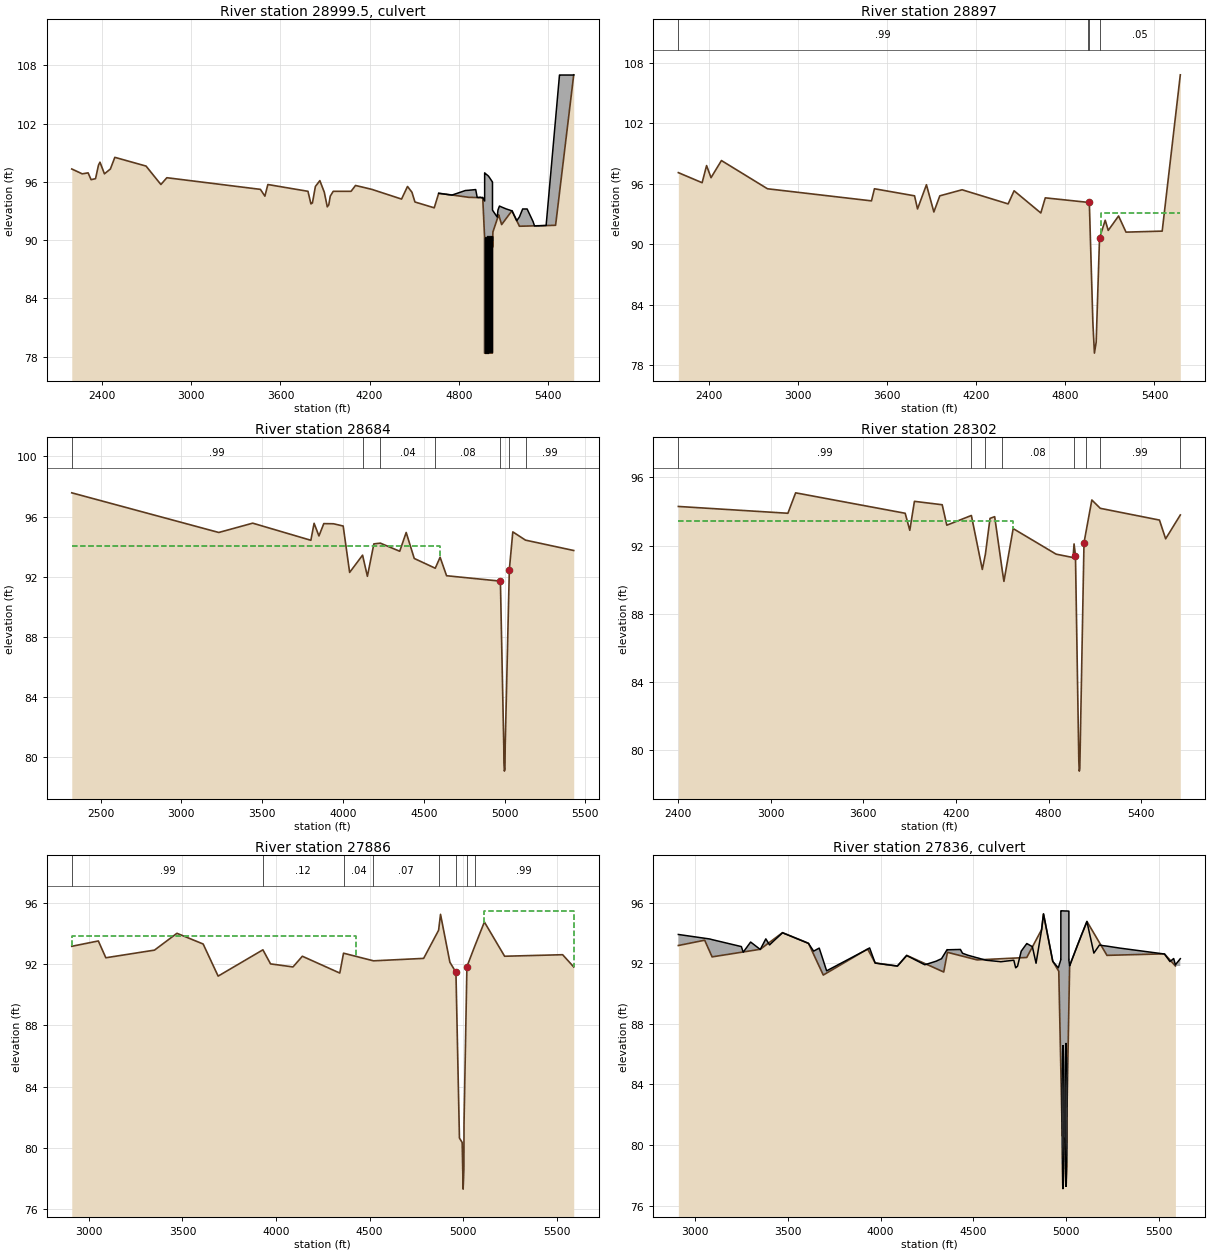
Type RM Length L Ch R = 2 ,28999.5 ,,,
BEGIN DESCRIPTION:
GESSNER
Structure ID: E117-00-00-14
END DESCRIPTION:
Bridge Culvert--1,0,-1,-1, 0
Deck Dist Width WeirC Skew NumUp NumDn MinLoCord MaxHiCord MaxSubmerge Is_Ogee
10,169,2.6,0, 48, 48, , , 0.95, 0, ,,,
  4665.2  4748.8  4754.2  4844.2  4867.6  4914.2  4924.2  4934.2  4944.4  4952.9
  4954.3  4961.6 4974.39  4974.5 4974.61  4985.7  4991.3  4992.4    4996  5000.6
  5004.1  5007.7  5009.2    5013 5027.09  5027.2 5027.31  5028.8  5030.3  5058.9
  5064.2  5068.6  5074.2  5088.9  5120.4  5158.5  5170.4  5190.4  5208.5  5230.4
  5260.4  5300.4  5310.4  5388.2  5452.1  5478.1  5478.2  5574.1
   94.81   94.64   94.63    95.1   95.13    95.2    94.4   94.37   94.41   94.36
   94.36   94.37   94.02   96.92   96.92   96.77    96.7   96.69   96.64   96.58
    96.5   96.42   96.39    96.3   95.98   95.98   93.08   93.05   93.01   92.37
    93.1   93.28    93.5    93.4    93.2   93.01   92.63   91.99   92.38    93.2
    93.2    91.9   91.45    91.5  102.51  106.98     107     107
                                                                                
                                                                                
                                                                                
                                                                                
                                                                
  4665.2  4748.8  4754.2  4844.2  4867.6  4914.2  4924.2  4934.2  4944.4  4952.9
  4954.3  4961.6 4974.39  4974.5 4974.61  4985.7  4991.3  4992.4    4996  5000.6
  5004.1  5007.7  5009.2    5013 5027.09  5027.2 5027.31  5028.8  5030.3  5058.9
  5064.2  5068.6  5074.2  5088.9  5120.4  5158.5  5170.4  5190.4  5208.5  5230.4
  5260.4  5300.4  5310.4  5388.2  5452.1  5478.1  5478.2  5574.1
   94.62   94.64   94.63    95.1   95.13    95.2    94.4   94.37   94.41   94.36
   94.36   94.37   94.02   96.92   96.92   96.77    96.7   96.69   96.64   96.58
    96.5   96.42   96.39    96.3   95.98   95.98   93.08   93.05   93.01   92.37
    93.1   93.28    93.5    93.4    93.2   93.01   92.63   91.99   92.38    93.2
    93.2    91.9   91.45    91.5  102.51  106.98     107     107
                                                                                
                                                                                
                                                                                
                                                                                
                                                                
BR Coef= 1 , 1 , 0 ,1.25, 0 ,,,0.8,-1,2,0,
WSPro=,,,, 1 ,,,, 0 ,,,, 0 ,,,,-1 ,-1 ,-1 , 0 , 0 , 0 , 0 , 0
Culvert=2,12,12,169,0.015,0.4,1,8,1,78.35,4979.8,78.42,4979.8,Culvert #1  , 0 ,10
Culvert Bottom n=0.015
Culvert=2,12,12,169,0.015,0.4,1,8,1,78.4,4993.4,78.39,4993.4,Culvert #2  , 0 ,10
Culvert Bottom n=0.015
Culvert=2,12,12,169,0.015,0.4,1,8,1,78.42,5007,78.36,5007,Culvert #3  , 0 ,10
Culvert Bottom n=0.015
Culvert=2,12,12,169,0.015,0.4,1,8,1,78.43,5020.6,78.46,5020.6,Culvert #4  , 0 ,10
Culvert Bottom n=0.015
BR U #Sta/Elev= 79
  2195.2   97.32  2248.8   96.94  2265.2   96.82  2305.2   96.92  2325.2   96.22
  2355.2   96.32  2375.2   97.72  2385.2   98.02  2415.2   96.82  2455.2   97.32
  2485.2   98.52  2695.2   97.62  2795.2   95.72  2835.2   96.42  2908.8   96.28
  3465.2   95.22  3495.2   94.52  3515.2   95.72  3785.2   95.02  3805.2   93.72
  3808.8   93.76  3815.2   93.82  3835.2   95.52  3865.2   96.12  3895.2   94.92
  3915.2   93.42  3925.2   93.62  3935.2   94.52  3955.2   95.02  4075.2   95.02
  4105.2   95.62    4150   95.46  4215.2   95.22  4415.2   94.22  4455.2   95.52
  4485.2   94.92  4505.2   93.92  4635.1   93.32  4635.2   93.32  4665.2   94.82
  4748.8   94.65  4754.2   94.64  4844.2   94.45  4867.6    94.4  4914.2   94.38
  4924.2   94.38  4934.2   94.38  4944.4   94.37  4952.9   94.37  4954.3   94.37
  4961.6   94.38  4973.8   90.35  4973.8   78.35  5026.6   78.35  5026.6   90.35
 5027.09   89.25  5027.2   89.31 5027.31   89.36  5028.8    90.1  5030.3   90.84
  5058.9   92.15  5064.2    92.4  5068.6    92.6  5074.2   92.32  5088.9   91.59
  5120.4   92.24  5158.5   93.02  5170.4   92.64  5190.4      92  5208.5   91.42
  5230.4   91.43  5260.4   91.44  5300.4   91.46  5310.4   91.46  5388.2   91.49
  5452.1   91.52  5478.1   94.82  5478.2   94.84  5574.1  107.02
BR U #Mann= 4
  2195.2     .99  4954.3     .04  4961.6    .015  5030.3     .05
BR D #Sta/Elev= 79
  2195.2   97.11  2248.8   96.73  2265.2   96.61  2305.2   96.71  2325.2   96.01
  2355.2   96.11  2375.2   97.51  2385.2   97.81  2415.2   96.61  2455.2   97.11
  2485.2   98.31  2695.2   97.41  2795.2   95.51  2835.2   96.21  2908.8   96.07
  3465.2   95.01  3495.2   94.31  3515.2   95.51  3785.2   94.81  3805.2   93.51
  3808.8   93.55  3815.2   93.61  3835.2   95.31  3865.2   95.91  3895.2   94.71
  3915.2   93.21  3925.2   93.41  3935.2   94.31  3955.2   94.81  4075.2   94.81
  4105.2   95.41    4150   95.25  4215.2   95.01  4415.2   94.01  4455.2   95.31
  4485.2   94.71  4505.2   93.71  4635.1   93.11  4635.2   93.11  4665.2   94.61
  4748.8   94.44  4754.2   94.43  4844.2   94.24  4867.6   94.19  4914.2   94.17
  4924.2   94.17  4934.2   94.17  4944.4   94.16  4952.9   94.16  4954.3   94.16
  4961.6   94.17  4973.8   90.35  4973.8   78.35  5026.6   78.35  5026.6   90.35
 5027.09   89.04  5027.2    89.1 5027.31   89.15  5028.8   89.89  5030.3   90.63
  5058.9   91.94  5064.2   92.19  5068.6   92.39  5074.2   92.11  5088.9   91.38
  5120.4   92.03  5158.5   92.81  5170.4   92.43  5190.4   91.79  5208.5   91.21
  5230.4   91.22  5260.4   91.23  5300.4   91.25  5310.4   91.25  5388.2   91.28
  5452.1   91.31  5478.1   94.61  5478.2   94.63  5574.1  106.81
BR D #Mann= 4
  2195.2     .99  4954.3     .04  4961.6    .015  5030.3     .05
BC Design=,, 0 ,, 0 ,,,,,,
BC HTab HWMax=107.02

Type RM Length L Ch R = 1 ,28897   ,222.1,213,211.3
BEGIN DESCRIPTION:
Gessner - 2
END DESCRIPTION:
XS GIS Cut Line= 3
      3064434.41     13882111.53      3064852.47     13879270.41
      3065198.94     13878904.32
#Sta/Elev= 30
  2195.2   97.11  2355.2   96.11  2385.2   97.81  2415.2   96.61  2485.2   98.31
  2795.2   95.51  3495.2   94.31  3515.2   95.51  3785.2   94.81  3805.2   93.51
  3865.2   95.91  3915.2   93.21  3955.2   94.81  4105.2   95.41  4415.2   94.01
  4455.2   95.31  4635.1   93.11  4665.2   94.61  4954.3   94.16  4961.6   94.17
  4985.7   82.17    4996   79.21  5007.7   80.29  5030.3   90.63  5068.6   92.39
  5088.9   91.38  5158.5   92.81  5208.5   91.21  5452.1   91.31  5574.1  106.81
#Mann= 4 ,-1 , 0
  2195.2     .99       0  4954.3     .04       0  4961.6    .015       0
  5030.3     .05       0
#XS Ineff= 2 , 0
       0    4959    93.4    5038       0    93.1
Permanent Ineff=
       F       F
Bank Sta=4961.6,5030.3
Exp/Cntr=0.5,0.3

Type RM Length L Ch R = 1 ,28684   ,444.7,382,370.4
BEGIN DESCRIPTION:
Gessner - 1
Interpolated channel, LIDAR overbanks
Right overbank spills to an unstudied ditch that flows into E117-00-00
END DESCRIPTION:
XS GIS Cut Line= 3
       3064664.4      13881973.4      3065073.31     13879194.77
      3065278.49     13878977.97
#Sta/Elev= 30
  2321.4   97.58  3231.4   94.94  3441.4   95.56  3801.4   94.42  3821.4   95.55
  3851.4   94.71  3881.4   95.53  3941.4   95.52  4001.4   95.37  4041.4   92.28
  4121.4   93.43  4151.4   92.02  4191.4   94.18  4231.4   94.23  4351.4   93.69
  4391.4   94.94  4441.4   93.21  4571.4   92.56  4601.4   93.29  4641.4   92.06
  4974.6    91.7  4995.6    80.7  4996.4   79.62  4999.3   79.05  5002.7   79.19
  5004.3   80.72  5029.9   92.46  5051.4   94.98    5130   94.43  5428.5   93.74
#Mann= 7 ,-1 , 0
  2321.4     .99       0  4121.4     .12       0  4231.4     .04       0
  4571.4     .08       0  4974.6     .04       0  5029.9     .05       0
    5130     .99       0
#XS Ineff= 2 , 0
         4603.28   94.07
Permanent Ineff=
       F       F
Bank Sta=4974.6,5029.9
Exp/Cntr=0.3,0.1

Type RM Length L Ch R = 1 ,28302   ,396,416,413.3
BEGIN DESCRIPTION:
Windfern - 4
Cross Section xs 22
Located At: US WINDFERN
END DESCRIPTION:
XS GIS Cut Line= 3
      3065082.75     13881943.18      3065509.31     13879746.08
      3065281.77     13878756.88
#Sta/Elev= 30
  2400.9    94.3  3110.9    93.9  3160.9    95.1  3870.9    93.9  3900.9    92.9
  3930.9    94.6  4110.9    94.4  4140.9    93.2    4300   93.77  4370.9    90.6
  4390.9    91.5  4420.9    93.6  4450.9    93.7  4500.9    90.5  4510.9    89.9
  4570.9      93    4849    91.5    4959    91.3  4965.5    92.1  4974.6   91.41
  4996.4   79.33  4999.3   78.76  5002.7    78.9  5029.9   92.17    5042   92.77
  5080.8   94.68  5135.4   94.19    5519    93.5    5559    92.4  5654.1    93.8
#Mann= 8 ,-1 , 0
  2400.9     .99       0    4300     .12       0  4390.9     .04       0
  4500.9     .08       0  4965.5     .04       0    5042     .05       0
  5135.4     .99       0  5654.1      .2       0
#XS Ineff= 2 , 0
         4570.01   93.44
Permanent Ineff=
       F       F
Bank Sta=4974.6,5029.9
Exp/Cntr=0.5,0.3

Type RM Length L Ch R = 1 ,27886   ,113.4,108,104.6
BEGIN DESCRIPTION:
Windfern - 3
Left overbank spills to E100-00-00.
Right overbank spills to an unstudied ditch that flows into E117-00-00
END DESCRIPTION:
XS GIS Cut Line= 3
      3065667.13       13881265.       3065753.9     13879174.26
      3065748.94     13878584.97
#Sta/Elev= 30
  2908.7   93.17  3050.7   93.52  3090.7   92.42  3350.7   92.92  3470.7   94.02
  3610.7   93.32  3690.7   91.22    3930   92.94  3970.7   92.02  4090.7   91.82
  4140.7   92.52  4340.7   91.42  4360.7   92.72  4520.7   92.22  4788.7   92.38
  4868.7   94.22  4878.9   95.26  4928.9   92.13  4961.3   91.47    4980   80.63
  4994.6   80.34  4999.7   77.29  5003.8   78.57  5004.5   81.59  5019.9   91.84
  5060.6   93.14  5113.2   94.76  5221.3   92.52  5531.3   92.62  5590.6   91.82
#Mann= 8 ,-1 , 0
  2908.7     .99       0    3930     .12       0  4360.7     .04       0
  4520.7     .07       0  4868.7     .08       0  4961.3     .04       0
  5019.9     .08       0  5060.6     .99       0
#XS Ineff= 2 , 0
       0 4425.52   93.87 5110.23       0   95.49
Permanent Ineff=
       F       F
Bank Sta=4961.3,5019.9
Exp/Cntr=0.5,0.3

Type RM Length L Ch R = 2 ,27836   ,,,
BEGIN DESCRIPTION:
WINDFERN
Structure ID: E117-00-00-13
END DESCRIPTION:
Bridge Culvert--1,0,-1,-1, 0
Deck Dist Width WeirC Skew NumUp NumDn MinLoCord MaxHiCord MaxSubmerge Is_Ogee
10,80,2.6,0, 118, 118, , , 0.95, 0, ,,,
  2908.7  3050.7  3078.7  3090.7  3248.7  3258.7  3298.7  3350.7  3368.7  3380.7
  3388.7  3400.7  3418.7  3448.7  3458.7  3470.7  3478.7  3488.7  3610.7  3628.7
  3638.7  3668.7  3670.7  3690.7  3708.7    3930  3938.7  3940.7  3970.7  4028.7
  4048.7  4090.7  4108.7  4140.7  4228.7  4238.7  4300.7  4310.7  4328.7  4340.7
  4358.7  4360.7  4430.7  4432.4  4441.9  4470.7  4520.7  4530.7  4540.7  4550.7
  4568.7  4648.7  4662.6  4690.7  4718.7  4720.7  4728.7  4730.7  4738.7  4742.7
  4750.7  4758.7  4760.7  4770.7  4788.7  4790.7  4810.7  4818.7  4820.7  4838.7
  4868.7  4878.9  4888.7  4928.9  4958.7  4961.3  4972.2  4972.3 4972.39  4972.5
 4972.61  4974.6    4980  4994.6  4997.1  4999.3  5001.5  5002.8  5004.5  5004.6
 5015.79  5015.9 5016.01  5016.1  5016.3  5019.9  5020.6  5030.6  5040.6  5050.6
  5060.6  5069.7  5080.6  5081.7  5113.2  5120.6  5150.6  5180.6  5191.3  5201.3
  5221.3  5290.6  5531.3  5561.3  5581.3  5590.5  5590.6  5617.1
    93.9   93.65    93.6   93.56    93.1   92.73    93.4   92.91   93.33   93.61
   93.45   93.21   93.42   93.76   93.87   94.01   93.97   93.92   93.31   92.98
    92.8      93   92.93   92.18    91.5   92.93      93   93.01   92.01   91.91
   91.88   91.81   92.06   92.51   91.96    91.9   92.14    92.2    92.3   92.54
    92.9   92.89   92.91   92.87   92.66   92.53   92.36   92.33   92.29   92.26
    92.2    92.1   92.12   92.16    92.2    92.1    91.7   91.72    91.8      92
    92.4    92.8   92.83      93    93.3   93.29   93.15    93.1   92.99      92
   94.21   95.25   94.64   92.12    91.7    91.8   92.23   92.26   92.26   95.46
   95.46   95.46   95.46   95.45   95.45   95.45   95.45   95.45   95.45   95.45
   95.44   95.44   92.24   92.24   92.18   91.83   91.85   92.17   92.49   92.81
   93.13   93.42   93.76    93.8   94.75   94.34   92.67    93.2   93.18   93.16
   93.13      93   92.61   92.11   92.31    91.9    91.9    92.3
                                                                                
                                                                                
                                                                                
                                                                                
                                                                                
                                                                                
                                                                                
                                                                                
                                                                                
                                                                                
                                                                                
                                                                
  2908.7  3050.7  3078.7  3090.7  3248.7  3258.7  3298.7  3350.7  3368.7  3380.7
  3388.7  3400.7  3418.7  3448.7  3458.7  3470.7  3478.7  3488.7  3610.7  3628.7
  3638.7  3668.7  3670.7  3690.7  3708.7    3930  3938.7  3940.7  3970.7  4028.7
  4048.7  4090.7  4108.7  4140.7  4228.7  4238.7  4300.7  4310.7  4328.7  4340.7
  4358.7  4360.7  4430.7  4432.4  4441.9  4470.7  4520.7  4530.7  4540.7  4550.7
  4568.7  4648.7  4662.6  4690.7  4718.7  4720.7  4728.7  4730.7  4738.7  4742.7
  4750.7  4758.7  4760.7  4770.7  4788.7  4790.7  4810.7  4818.7  4820.7  4838.7
  4868.7  4878.9  4888.7  4928.9  4958.7  4961.3  4972.2  4972.3 4972.39  4972.5
 4972.61  4974.6    4980  4994.6  4997.1  4999.3  5001.5  5002.8  5004.5  5004.6
 5015.79  5015.9 5016.01  5016.1  5016.3  5019.9  5020.6  5030.6  5040.6  5050.6
  5060.6  5069.7  5080.6  5081.7  5113.2  5120.6  5150.6  5180.6  5191.3  5201.3
  5221.3  5290.6  5531.3  5561.3  5581.3  5590.5  5590.6  5617.1
    93.9   93.65    93.6   93.56    93.1   92.73    93.4   92.91   93.33   93.61
   93.45   93.21   93.42   93.76   93.87   94.01   93.97   93.92   93.31   92.98
    92.8      93   92.93   92.18    91.5   92.93      93   93.01   92.01   91.91
   91.88   91.81   92.06   92.51   91.96    91.9   92.14    92.2    92.3   92.54
    92.9   92.89   92.91   92.87   92.66   92.53   92.36   92.33   92.29   92.26
    92.2    92.1   92.12   92.16    92.2    92.1    91.7   91.72    91.8      92
    92.4    92.8   92.83      93    93.3   93.29   93.15    93.1   92.99      92
   94.21   95.25   94.64   92.12    91.7    91.8   92.23   92.26   92.26   95.46
   95.46   95.46   95.46   95.45   95.45   95.45   95.45   95.45   95.45   95.45
   95.44   95.44   92.24   92.24   92.18   91.83   91.85   92.17   92.49   92.81
   93.13   93.42   93.76    93.8   94.75   94.34   92.67    93.2   93.18   93.16
   93.13      93   92.61   92.11   92.31    91.9    91.9    92.3
                                                                                
                                                                                
                                                                                
                                                                                
                                                                                
                                                                                
                                                                                
                                                                                
                                                                                
                                                                                
                                                                                
                                                                
BR Coef= 1 , 1 , 0 ,1.25, 0 ,,,0.8,0,2,0,
WSPro=,,,, 1 ,,,, 0 ,,,, 0 ,,,,-1 ,-1 ,-1 , 0 , 0 , 0 , 0 , 0
Culvert=1,9.5,,80,0.033,0.5,1,1,3,77.09,4984,77.61,4984,Culvert #1  , 0 ,10
Culvert Bottom n=0.033
Culvert=1,9.5,,80,0.015,0.5,1,1,3,77.24,5000.5,77.52,5000.5,Culvert #2  , 0 ,10
Culvert Bottom n=0.015
BC Design=,, 0 ,, 0 ,,,,,,
BC HTab HWMax=95.26

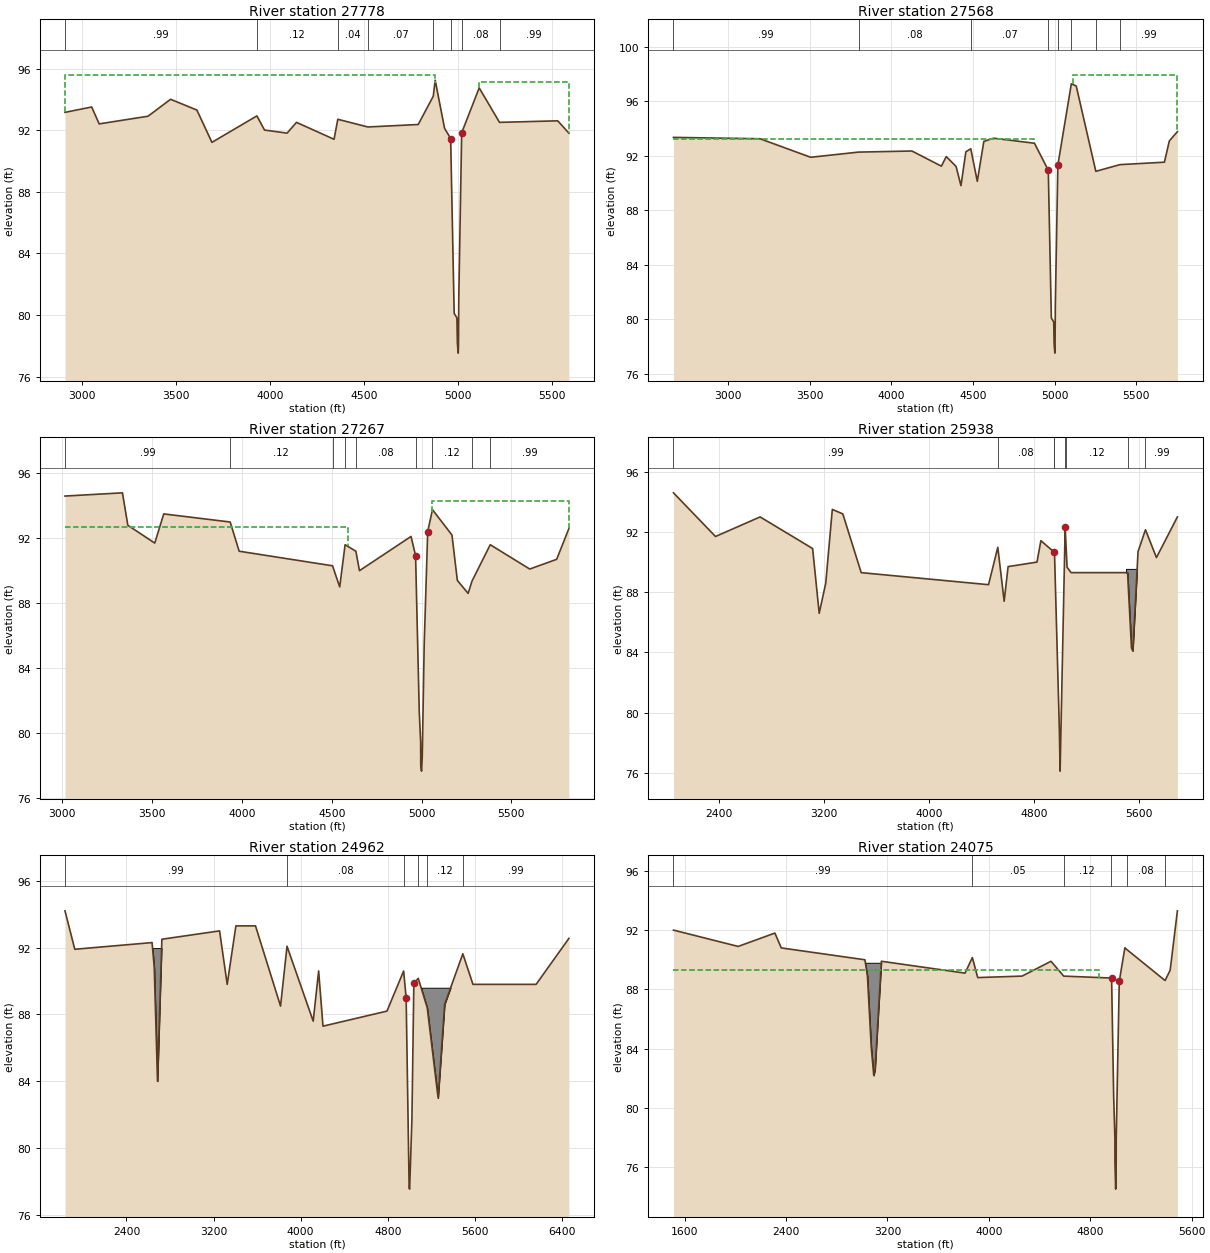
Type RM Length L Ch R = 1 ,27778   ,215.4,210,202.9
BEGIN DESCRIPTION:
Windfern - 2
Left overbank spills to E100-00-00
Right overbank spills to an unstudied ditch that flows into E117-00-00
END DESCRIPTION:
XS GIS Cut Line= 3
 3065769.440337613881266.1030697      3065856.21     13879175.18
      3065851.25     13878585.76
#Sta/Elev= 30
  2908.7   93.17  3050.7   93.52  3090.7   92.42  3350.7   92.92  3470.7   94.02
  3610.7   93.32  3690.7   91.22    3930   92.94  3970.7   92.02  4090.7   91.82
  4140.7   92.52  4340.7   91.42  4360.7   92.72  4520.7   92.22  4788.7   92.38
  4868.7   94.22  4878.9   95.26  4928.9   92.13  4961.3   91.47    4980    80.1
  4994.6   79.81  4997.1   78.16  5001.5   77.52  5002.8   78.04  5004.5   81.06
  5019.9   91.84  5113.2   94.76  5221.3   92.52  5531.3   92.62  5590.6   91.82
#Mann= 8 ,-1 , 0
  2908.7     .99       0    3930     .12       0  4360.7     .04       0
  4520.7     .07       0  4868.7     .08       0  4961.3     .04       0
  5019.9     .08       0  5221.3     .99       0
#XS Ineff= 2 , 0
       0 4877.36   95.61  5113.7       0   95.17
Permanent Ineff=
       F       F
Bank Sta=4961.3,5019.9
Exp/Cntr=0.5,0.3

Type RM Length L Ch R = 1 ,27568   ,305,301,296.2
BEGIN DESCRIPTION:
Windfern - 1
Interpolated channel, LIDAR overbanks
END DESCRIPTION:
XS GIS Cut Line= 3
      3065961.89      13881452.2      3066056.24     13879178.48
       3066051.9     13878369.06
#Sta/Elev= 30
  2666.7   93.35  3196.7   93.25  3506.7   91.89    3800   92.27  4126.7   92.35
  4306.7   91.24  4336.7   91.94  4396.7   91.22  4426.7   89.81  4456.7   92.29
  4486.7   92.52  4526.7   90.13  4566.7   93.05  4626.7   93.29  4876.7   92.92
  4961.3   90.94    4980    80.1  4994.6   79.81  4997.1   78.16  5001.5   77.52
  5002.8   78.04  5004.5   81.06  5019.9   91.31  5102.4   97.28  5132.4   97.12
  5252.4   90.86    5400   91.35  5672.4   91.53  5702.4   93.09  5751.8   93.77
#Mann= 8 ,-1 , 0
  2666.7     .99       0    3800     .08       0  4486.7     .07       0
  4961.3     .04       0  5019.9     .04       0  5102.4     .12       0
  5252.4     .05       0    5400     .99       0
#XS Ineff= 2 , 0
         4873.88    93.2 5110.23           97.94
Permanent Ineff=
       F       F
Bank Sta=4961.3,5019.9
Exp/Cntr=0.3,0.1

Type RM Length L Ch R = 1 ,27267   ,1347.1,1329,1347.6
BEGIN DESCRIPTION:
Cross Section XS21
Left overbank spills to E117
Located At: DS WINDFERN
END DESCRIPTION:
XS GIS Cut Line= 4
      3066360.98     13881049.35      3066378.79     13879324.31
      3066311.76     13878684.69      3066338.02     13878247.29
#Sta/Elev= 30
  3014.5    94.6  3334.5    94.8  3364.5    92.8  3514.5    91.7  3564.5    93.5
  3934.5      93  3984.5    91.2  4504.5    90.3  4544.5      89  4574.5    91.6
  4634.5    91.2  4654.5      90  4941.7   92.11    4967   90.93  4987.6   81.25
  4995.3   79.41  4995.6   78.01  5000.1   77.64  5004.2   78.51    5015   85.44
  5034.5   92.41  5061.1   93.76  5169.6    92.2  5199.6    89.4  5259.6    88.6
  5281.3   89.36  5382.8    91.6  5602.8    90.1  5752.8    90.7  5820.9    92.6
#Mann= 9 ,-1 , 0
  3014.5     .99       0  3934.5     .12       0  4504.5     .08       0
  4574.5     .04       0  4634.5     .08       0    4967     .04       0
  5061.1     .12       0  5281.3     .08       0  5382.8     .99       0
#XS Ineff= 2 , 0
       0 4590.86   92.68 5058.59       0   94.32
Permanent Ineff=
       F       F
Bank Sta=4967,5034.5
Exp/Cntr=0.3,0.1

Type RM Length L Ch R = 1 ,25938   ,964.4,976,967.5
BEGIN DESCRIPTION:
Cross Section XS20
Located At: 2ND DS WINDFERN
END DESCRIPTION:
XS GIS Cut Line= 3
      3066912.05     13881155.33      3067693.81      13878781.6
      3067023.91     13877621.45
#Sta/Elev= 30
  2054.4    94.6  2374.4    91.7  2714.4      93  3114.4    90.9  3164.4    86.6
  3214.4    88.6  3264.4    93.5  3344.4    93.2  3484.4    89.3  4454.4    88.5
    4525   90.98  4573.5    87.4  4603.5    89.7  4823.5      90  4853.2   91.42
  4954.8   90.66  4956.9   90.64  4994.1   78.84  4999.6   76.12  5038.2    92.3
  5045.7   90.93  5052.7   89.66  5083.5    89.3  5513.5    89.3  5543.5    84.3
  5553.5    84.1  5593.5    90.7    5650   92.15  5733.5    90.3  5893.2      93
#Mann= 8 ,-1 , 0
  2054.4     .99       0    4525     .08       0  4954.8     .04       0
  4956.9     .04       0  5038.2     .04       0  5045.7     .12       0
  5513.5     .04       0    5650     .99       0
#Block Obstruct= 1 ,-1
 5501.45 5597.16   89.55
Bank Sta=4956.9,5038.2
Exp/Cntr=0.3,0.1

Type RM Length L Ch R = 1 ,24962   ,865.6,887,909.9
BEGIN DESCRIPTION:
Cross Section XS19
Right overbank has small ditch from road drainage. Left overbank has a detention pond
Located At: 2ND FAIRBANKS N-HOUSTON
END DESCRIPTION:
XS GIS Cut Line= 4
      3067955.91      13880916.8      3068461.55     13878206.06
       3067694.9     13876808.33 3067548.431724713876583.7042388
#Sta/Elev= 30
  1835.4    94.2  1925.4    91.9  2635.4    92.3  2655.4    90.8  2685.4      84
  2725.4    92.5  3255.4      93  3325.4    89.8  3405.4    93.3  3585.4    93.3
  3815.4    88.5    3875   92.08  4115.4    87.6  4165.4    90.6  4205.4    87.3
    4793    88.2  4946.2    90.6  4969.3   88.99  4996.8   77.62  5001.3   77.55
  5022.3   81.77  5039.9   89.87  5080.5   90.16    5163    88.4    5263      83
    5323    88.6    5490   91.63    5583    89.8    6163    89.8  6464.3   92.55
#Mann= 6 ,-1 , 0
  1835.4     .99       0    3875     .08       0  4946.2     .04       0
  5080.5     .08       0    5163     .12       0    5490     .99       0
#Block Obstruct= 2 ,-1
 2632.78 2765.17   91.97 5113.61 5416.04    89.6
Bank Sta=4969.3,5039.9
Exp/Cntr=0.3,0.1

Type RM Length L Ch R = 1 ,24075   ,738.4,728,737.4
BEGIN DESCRIPTION:
Cross Section XS18
Detention pond on left overbank
END DESCRIPTION:
XS GIS Cut Line= 3
      3068824.91     13880906.28      3069284.98     13878045.08
      3068877.62     13877047.93
#Sta/Elev= 30
  1512.5      92  2022.6    90.9  2312.6    91.8  2362.6    90.8  3022.6      90
  3042.6    88.9  3072.6    84.1  3092.6    82.2  3102.6    82.6  3152.6    89.9
  3812.6    89.1    3870   90.15  3912.6    88.8  4262.6    88.9  4490.6    89.9
  4590.6    88.9    4963   88.77  4968.5    88.8    4985   80.75  4994.7   77.96
  4994.9   76.41  5000.8   74.54  5004.4   75.51  5005.2      78    5029   88.54
  5073.4   90.81  5090.2   90.68  5390.6    88.6  5430.6    89.3  5487.7    93.3
#Mann= 6 ,-1 , 0
  1512.5     .99       0    3870     .05       0  4590.6     .12       0
    4963     .04       0  5090.2     .08       0  5390.6     .04       0
#XS Ineff= 2 , 0
         4869.19   89.29
Permanent Ineff=
       F       F
#Block Obstruct= 1 ,-1
 3009.46 3178.88    89.8
Bank Sta=4968.5,5029
Exp/Cntr=0.3,0.1

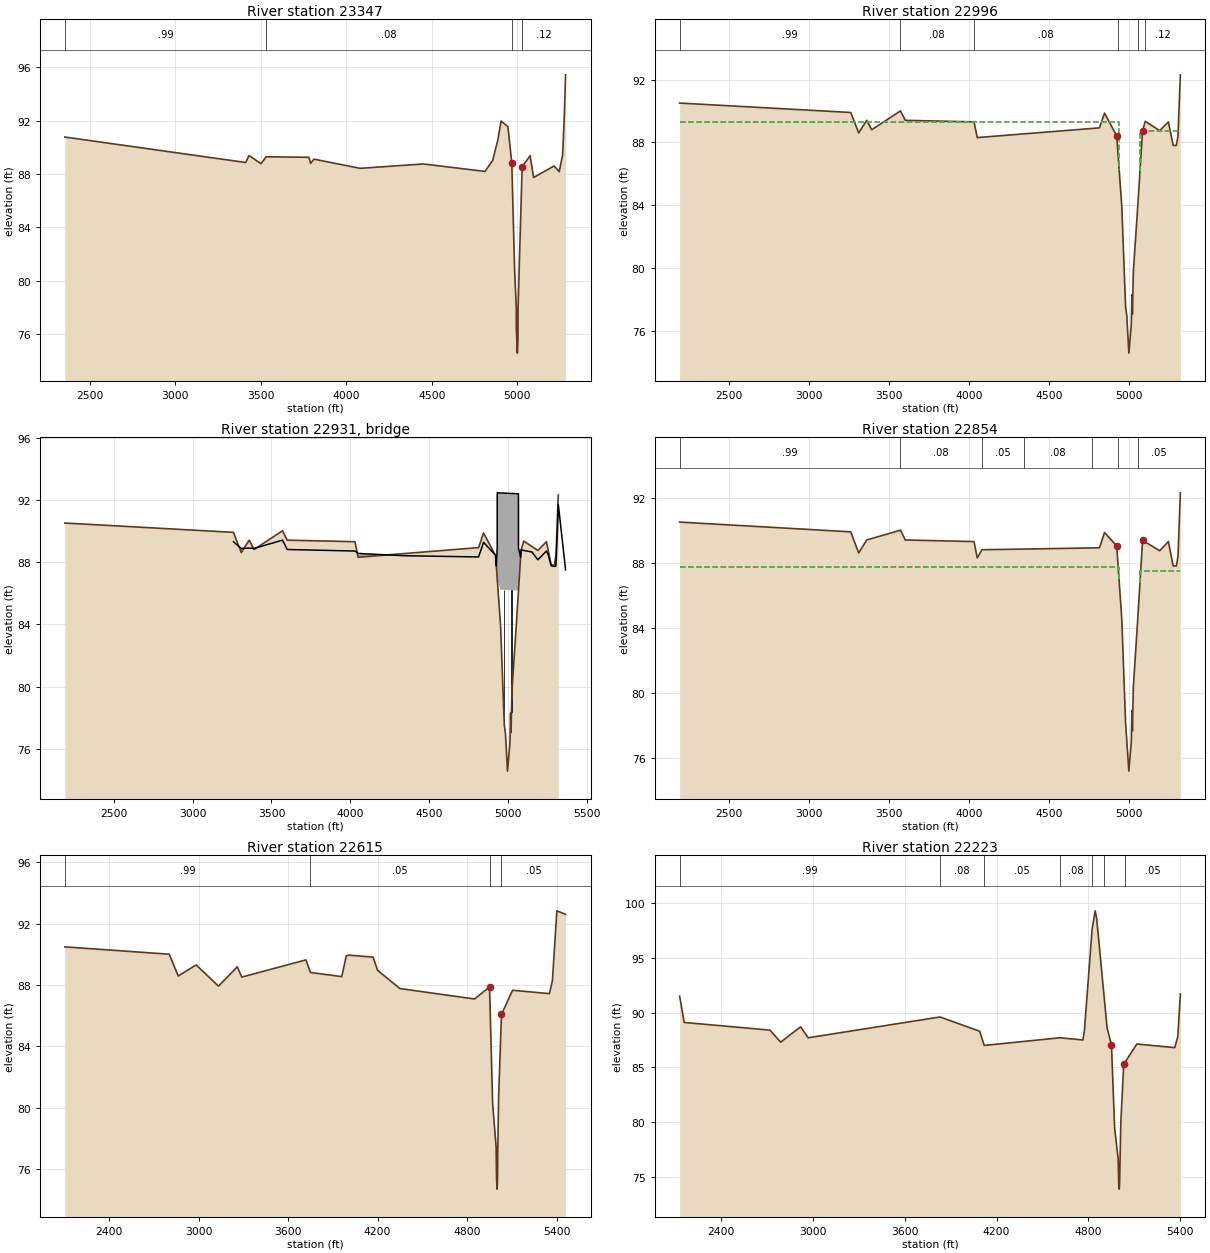
Type RM Length L Ch R = 1 ,23347   ,331.9,351,379
BEGIN DESCRIPTION:
Fairbanks Houston - 4
Interpolated channel, LIDAR overbanks
END DESCRIPTION:
XS GIS Cut Line= 4
       3069701.2      13879692.7      3069611.53     13878638.85
      3069700.55     13877217.39      3069473.85     13876831.76
#Sta/Elev= 30
  2353.8   90.78  3411.5   88.87  3431.5   89.39  3501.5   88.78  3531.5    89.3
  3781.5   89.26  3791.5    88.8  3811.5   89.12  4081.5   88.43  4451.5   88.76
  4811.5    88.2  4855.8   89.01  4885.8    90.5  4905.8   91.98  4945.8   91.56
  4968.5   88.82    4985   80.77  4994.7   77.98  4994.9   76.43  5000.8   74.56
  5004.4   75.53  5005.2   78.02    5029   88.56  5075.8   89.38  5095.8   87.74
  5215.8   88.61  5245.8   88.18  5265.8   89.43  5275.8   92.43  5283.1   95.45
#Mann= 4 ,-1 , 0
  2353.8     .99       0  3531.5     .08       0  4968.5     .04       0
    5029     .12       0
Bank Sta=4968.5,5029
Exp/Cntr=0.5,0.3

Type RM Length L Ch R = 1 ,22996   ,137.6,142,136
BEGIN DESCRIPTION:
Fairbanks Houston  - 3
END DESCRIPTION:
XS GIS Cut Line= 5
      3069908.1213879765.5087394      3069812.06     13878636.61
      3069916.55     13876968.14       3069936.2     13876751.28
 3069916.499843713876643.9217302
#Sta/Elev= 30
  2188.5   90.51  3258.5   89.91  3308.5   88.61  3358.5   89.41  3389.7   88.81
  3569.7   90.01  3599.7   89.41  4029.7   89.31  4049.7   88.31  4814.2   88.93
  4845.7   89.87  4921.9   88.42  4932.2   86.97  4953.8   83.92  4977.4   77.53
  4984.9   76.96  4997.9   74.57  5013.1   76.36  5017.4    78.3  5020.1   77.05
  5025.7   79.71  5053.4   83.92  5083.7   88.76  5100.8   89.35  5190.4   88.75
  5245.1   89.31  5275.1   87.81  5295.1   87.81  5305.1   88.41  5320.1   92.31
#Mann= 6 ,-1 , 0
  2188.5     .99       0  3569.7     .08       0  4029.7     .08       0
  4932.2     .04       0  5053.4     .05       0  5100.8     .12       0
#XS Ineff= 2 , 0
       0 4937.35   89.32 5067.42       0   88.76
Permanent Ineff=
       F       F
Bank Sta=4921.9,5083.7
Exp/Cntr=0.5,0.3

Type RM Length L Ch R = 3 ,22931   ,,,
BEGIN DESCRIPTION:
FAIRBANKS-N HOUSTON
Structure ID: E117-00-00-12
END DESCRIPTION:
Bridge Culvert--1,0,-1,-1, 0
Deck Dist Width WeirC Skew NumUp NumDn MinLoCord MaxHiCord MaxSubmerge Is_Ogee
10,110,2.6,0, 35, 35, , , 0.95, 0, ,,,
  3258.5  3308.5  3358.5  3389.7  3569.7  3599.7  4029.7  4049.7  4069.7  4079.7
  4343.8  4814.2  4845.7  4921.9  4926.8 4932.39  4932.5 4932.81  4932.9  5067.3
 5067.41  5067.5  5080.8  5083.7  5152.4  5190.4  5245.1  5255.1  5275.1  5295.1
    5304  5305.1  5315.1  5320.1  5366.3
   89.31   88.87    88.9   88.88   89.41   88.81   88.71   88.56   88.55   88.54
   88.41   88.33   89.27   88.44   87.75   88.95   92.45   92.45   92.45   92.39
   88.89   88.89   88.32   88.78   88.65   88.15   88.71   88.51   87.76   87.72
   87.74   87.81   90.21   91.71    87.5
   89.29   87.99   88.79   88.19   89.39   88.79   88.69   87.69   87.79   88.19
   88.23   88.31   89.25   88.42   87.73   86.94   86.92   86.88   86.23   86.18
   86.18   86.18    88.3   88.76   88.63   88.13   88.69   88.49   87.19   87.19
   87.72   87.79   90.19   91.69   87.49
  3258.5  3308.5  3358.5  3389.7  3569.7  3599.7  4029.7  4049.7  4069.7  4079.7
  4343.8  4814.2  4845.7  4921.9  4926.8 4932.39  4932.5 4932.81  4932.9  5067.3
 5067.41  5067.5  5080.8  5083.7  5152.4  5190.4  5245.1  5255.1  5275.1  5295.1
    5304  5305.1  5315.1  5320.1  5366.3
   89.31   88.87    88.9   88.88   89.41   88.81   88.71   88.56   88.55   88.54
   88.41   88.33   89.27   88.44   87.75   88.95   92.45   92.45   92.45   92.39
   88.89   88.89   88.32   88.78   88.65   88.15   88.71   88.51   87.76   87.72
   87.74   87.81   90.21   91.71    87.5
   89.29   87.99   88.79   88.19   89.39   88.79   88.69   87.69   87.79   88.19
   88.23   88.31   89.25   88.42   87.73   86.94   86.92   86.88   86.23   86.18
   86.18   86.18    88.3   88.76   88.63   88.13   88.69   88.49   87.19   87.19
   87.72   87.79   90.19   91.69   87.49
Pier Skew, UpSta & Num, DnSta & Num=  ,4977.4, 2 ,4977.4, 2 , 0 , 0 , 0 ,,
     1.5     1.5
   76.47   87.22
     1.5     1.5
   77.11   87.86
Pier Skew, UpSta & Num, DnSta & Num=  ,5022.9, 2 ,5022.9, 2 , 0 , 0 , 0 ,,
     1.5     1.5
   76.84    87.2
     1.5     1.5
   77.48   87.84
BR Coef= 1 , 1 , 0 ,1.25, 0 ,,,0.8,-1,2,0,
WSPro=,,,, 1 ,,,, 0 ,,,, 0 ,,,,-1 ,-1 ,-1 , 0 , 0 , 0 , 0 , 0
BC Design=,, 0 ,, 0 ,,,,,,
BC HTab HWMax=91.69

Type RM Length L Ch R = 1 ,22854   ,250.8,239,209.7
BEGIN DESCRIPTION:
Fairbanks Houston - 2
END DESCRIPTION:
XS GIS Cut Line= 5
       3070038.113879717.8986854      3069941.84     13878586.65
       3070046.3     13876918.62        3070066.     13876701.15
  3070046.77397313876596.3581045
#Sta/Elev= 30
  2188.5   90.51  3258.5   89.91  3308.5   88.61  3358.5   89.41  3569.7   90.01
  3599.7   89.41  4029.7   89.31  4049.7   88.31  4079.7   88.81  4343.8   88.85
  4766.8   88.92  4814.2   88.93  4845.7   89.87  4921.9   89.04  4932.2   87.59
  4953.8   84.54  4977.4   78.15  4997.9   75.19  5013.1   76.98  5017.4   78.92
  5020.1   77.67  5025.7   80.33  5053.4   84.54  5083.7   89.38  5190.4   88.75
  5245.1   89.31  5275.1   87.81  5295.1   87.81  5305.1   88.41  5320.1   92.31
#Mann= 7 ,-1 , 0
  2188.5     .99       0  3569.7     .08       0  4079.7     .05       0
  4343.8     .08       0  4766.8     .05       0  4932.2     .04       0
  5053.4     .05       0
#XS Ineff= 2 , 0
       0 4937.35   87.75 5067.42       0    87.5
Permanent Ineff=
       F       F
Bank Sta=4921.9,5083.7
Exp/Cntr=0.5,0.3

Type RM Length L Ch R = 1 ,22615   ,397.4,392,376.9
BEGIN DESCRIPTION:
Fairbanks Houston - 1
Interpolated channel, LIDAR overbanks
END DESCRIPTION:
XS GIS Cut Line= 6
      3070277.59      13879700.5      3070175.57     13878579.19
      3070280.57     13876929.15      3070228.95     13876713.79
      3070233.21     13876577.14      3070176.94      13876366.1
#Sta/Elev= 30
  2104.1   90.49  2804.1   90.01  2864.1   88.59  2984.1   89.31  3134.1   87.93
    3260   89.19    3290   88.52    3720   89.64    3750   88.82    3960   88.55
    3990    89.9    4010   89.95    4170   89.82    4200   88.96    4350   87.77
    4850   87.09  4950.5   87.88  4971.2   80.25  4994.3   77.45  4997.6   75.27
    5001   74.69  5003.5   75.18  5005.7    77.4  5011.4   80.72  5030.4   86.08
  5104.9   87.66  5351.6   87.44  5371.6   88.28  5401.6   92.84    5460   92.61
#Mann= 4 ,-1 , 0
  2104.1     .99       0    3750     .05       0  4950.5     .04       0
  5030.4     .05       0
Bank Sta=4950.5,5030.4
Exp/Cntr=0.3,0.1

Type RM Length L Ch R = 1 ,22223   ,1004.4,943,757.9
BEGIN DESCRIPTION:
Cross Section XS17
Located At: DS FAIRBANKS N-HOUSTON
END DESCRIPTION:
XS GIS Cut Line= 3
      3071336.9813879433.8680137      3070726.21     13877025.61
      3070450.88     13876288.71
#Sta/Elev= 30
  2129.4    91.5  2159.4    89.1  2719.4    88.4  2789.4    87.3  2919.4    88.7
  2969.4    87.7    3830    89.6  4089.4    88.3  4119.4      87  4613.9    87.7
  4763.9    87.5  4773.9    88.4  4823.9    97.6  4843.9    99.3  4853.9    98.6
  4898.5   92.04  4921.9    88.6  4950.5   87.06  4971.2   79.43  4994.3   76.63
  4997.6   74.45    5001   73.87  5003.5   74.36  5011.4    79.9  5030.4   85.26
  5040.4   85.49  5116.3   87.13  5363.9    86.8  5383.9    87.8  5400.6    91.7
#Mann= 7 ,-1 , 0
  2129.4     .99       0    3830     .08       0  4119.4     .05       0
  4613.9     .08       0  4823.9     .05       0  4898.5     .04       0
  5040.4     .05       0
Bank Sta=4950.5,5030.4
Exp/Cntr=0.3,0.1

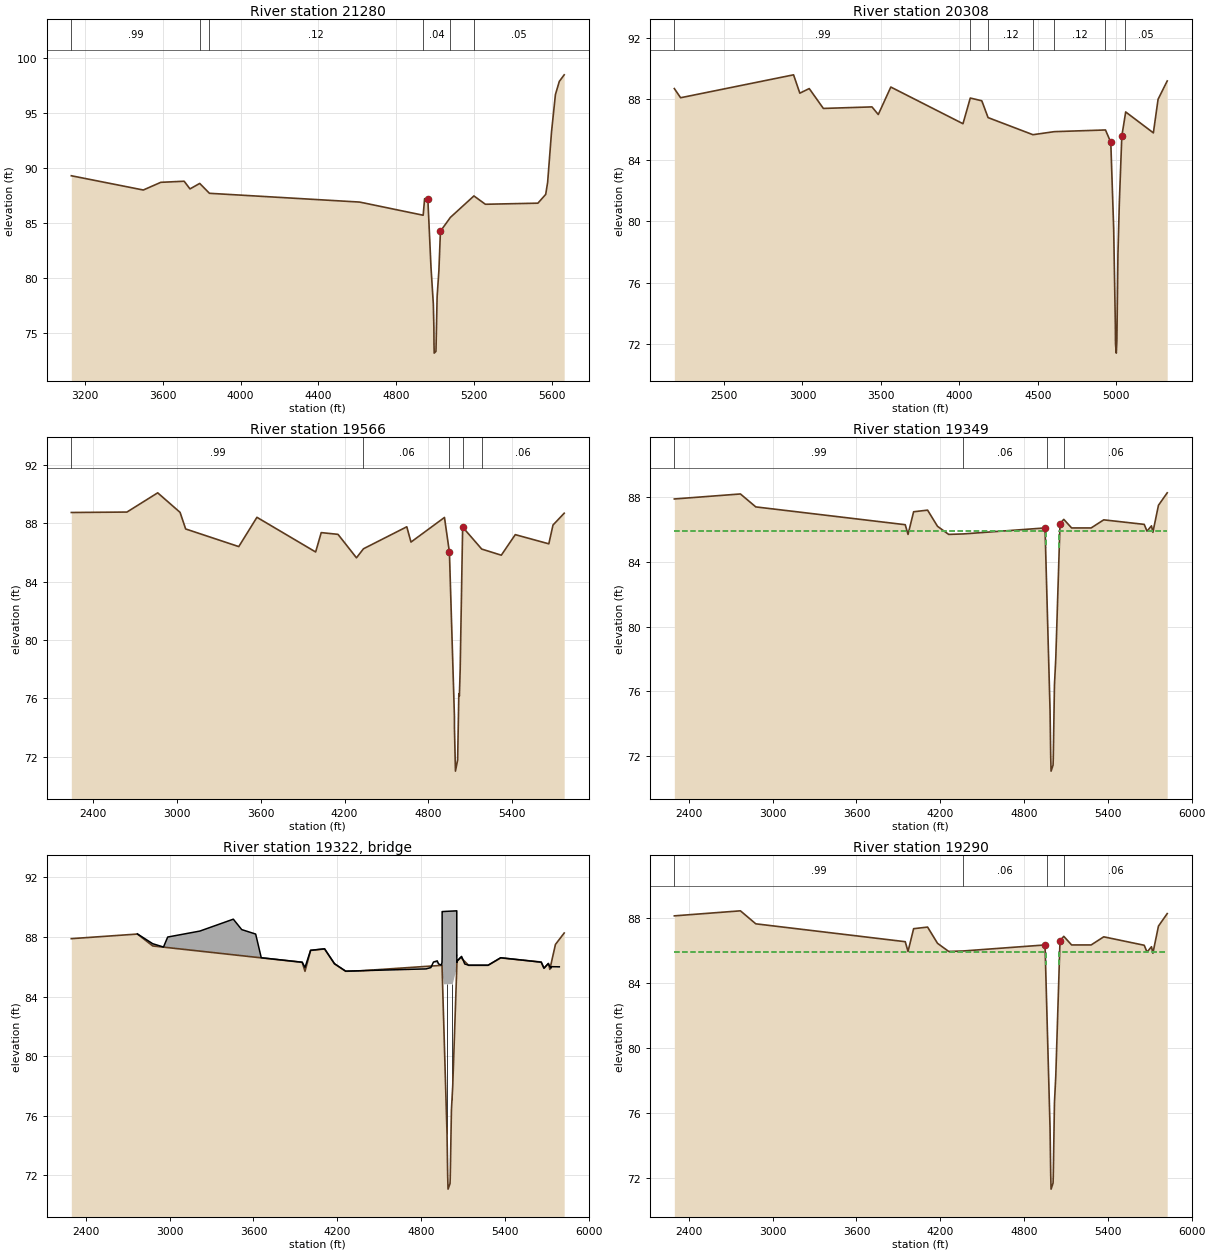
Type RM Length L Ch R = 1 ,21280   ,938.8,972,951.1
BEGIN DESCRIPTION:
Cross Section XS16
Located At: 2ND US GUHN
END DESCRIPTION:
XS GIS Cut Line= 5
      3071919.02      13878099.5      3071663.54     13876639.75
      3071476.15     13876450.24      3071389.01     13876368.24
      3070904.65     13875912.44
#Sta/Elev= 30
  3130.3    89.3  3500.3      88  3590.3    88.7  3710.3    88.8  3740.3    88.1
  3790.3    88.6  3840.3    87.7  4612.3    86.9  4938.8    85.7  4946.2   87.21
  4962.8   87.18    4979   80.96    4991   77.61  4993.8   75.49  4994.5   73.93
  4995.5   73.13  5004.5   73.29  5010.5   78.29  5019.6   80.65  5027.5   84.24
  5078.5    85.5  5199.6   87.46  5258.5    86.7  5528.5    86.8  5568.5    87.6
  5578.5    88.7  5598.5    93.3  5618.5    96.7  5638.5    97.9  5663.6    98.5
#Mann= 6 ,-1 , 0
  3130.3     .99       0  3790.3     .08       0  3840.3     .12       0
  4938.8     .04       0  5078.5      .1       0  5199.6     .05       0
Bank Sta=4962.8,5027.5
Exp/Cntr=0.3,0.1

Type RM Length L Ch R = 1 ,20308   ,744.9,742,719.7
BEGIN DESCRIPTION:
Cross Section XS15
Highest ground on left and right overbanks.
Located At: US GUHN
END DESCRIPTION:
XS GIS Cut Line= 4
      3072256.3913878434.2904631      3072128.21     13876204.31
      3071841.49      13875372.4      3071832.41     13875345.47
#Sta/Elev= 30
  2183.4    88.7  2223.4    88.1  2943.4    89.6  2983.4    88.4  3043.4    88.7
  3133.4    87.4  3443.4    87.5  3483.4      87  3563.4    88.8  4023.4    86.4
    4070   88.08  4143.4    87.9  4183.4    86.8  4469.3   85.68  4605.8   85.88
  4931.9   85.99  4965.7   85.18  4984.1   79.54  4994.7   73.23  4995.7      72
  5000.7   71.38  5004.4   72.14  5011.3   77.87    5020   81.18  5035.9   85.58
  5054.3   86.76  5060.6   87.17  5237.1    85.8  5267.1      88  5325.4    89.2
#Mann= 7 ,-1 , 0
  2183.4     .99       0    4070     .07       0  4183.4     .12       0
  4469.3     .05       0  4605.8     .12       0  4931.9     .04       0
  5054.3     .05       0
Bank Sta=4965.7,5035.9
Exp/Cntr=0.3,0.1

Type RM Length L Ch R = 1 ,19566   ,197.5,217,252.3
BEGIN DESCRIPTION:
Guhn - 4
Interpolated channel, LIDAR overbanks
END DESCRIPTION:
XS GIS Cut Line= 6
      3072360.92      13878335.5      3072322.34     13877939.33
      3072673.01     13876406.91      3072684.12     13875717.37
      3072570.94     13875569.13      3072571.29      13874889.1
#Sta/Elev= 30
  2245.1   88.75  2643.2   88.78  2863.2    90.1  3023.2   88.76  3063.2   87.62
  3443.2   86.41  3573.2   88.42  3993.2   86.04  4033.2   87.37  4153.2   87.25
  4285.3   85.64  4335.3   86.26  4645.3   87.77  4675.3   86.72  4914.9   88.41
  4950.2   86.03  4986.1   74.75  4986.2   73.99  4993.4      71  5009.1   71.77
  5017.6   76.31  5021.5   76.15  5027.2   77.96  5044.9   87.75  5181.4   86.24
  5321.4   85.82  5421.4   87.23  5661.4    86.6  5691.4   87.89  5771.4    88.7
#Mann= 5 ,-1 , 0
  2245.1     .99       0  4335.3     .06       0  4950.2     .04       0
  5044.9     .12       0  5181.4     .06       0
Bank Sta=4950.2,5044.9
Exp/Cntr=0.5,0.3

Type RM Length L Ch R = 1 ,19349   ,59.8,59,58.4
BEGIN DESCRIPTION:
Guhn - 3
Right overbank spills to E115-04
END DESCRIPTION:
XS GIS Cut Line= 5
 3072406.688799613878257.5610066      3072801.16     13876415.96
        3072853.      13874882.4      3072852.65       13874834.
      3072852.19      13874771.3
#Sta/Elev= 30
  2296.1   87.89  2769.3    88.2  2879.3    87.4  3949.3    86.3  3969.3    85.7
  4009.3    87.1  4109.3    87.2  4180.4    86.2  4260.4    85.7  4365.9   85.73
  4950.2    86.1  4964.4   81.64  4986.1   74.82  4990.8   71.99  4993.4   71.07
  5007.6   71.44  5009.1   71.84  5017.6   76.38  5027.1   78.03  5057.5   86.37
  5084.4   86.63  5140.4    86.1  5280.4    86.1  5370.4    86.6  5660.4   86.32
  5680.4    85.9  5712.3   86.23  5722.3   85.83  5762.3    87.5    5825   88.27
#Mann= 4 ,-1 , 0
  2296.1     .99       0  4365.9     .06       0  4964.4     .04       0
  5084.4     .06       0
#XS Ineff= 2 , 0
       0 4954.06   85.91 5051.96       0   85.91
Permanent Ineff=
       F       F
Bank Sta=4950.2,5057.5
Exp/Cntr=0.5,0.3

Type RM Length L Ch R = 3 ,19322   ,,,
BEGIN DESCRIPTION:
GUHN
Structure ID: E117-11
END DESCRIPTION:
Bridge Culvert--1,0,-1,-1, 0
Deck Dist Width WeirC Skew NumUp NumDn MinLoCord MaxHiCord MaxSubmerge Is_Ogee
10,34,2.6,0, 44, 44, , , 0.95, 0, ,,,
  2769.3  2879.3  2956.1  2986.1  3216.1  3456.1  3516.1  3616.1  3656.1  3949.3
  3969.3  4009.3  4109.3  4180.4  4260.4  4835.9  4870.5    4889  4915.9  4925.9
  4945.9  4950.2 4950.97 4951.08 4951.31  4951.4 5055.89    5056 5056.11  5056.3
  5056.4  5057.2  5057.5  5090.4  5112.9  5140.4  5280.4  5370.4  5660.4  5680.4
  5710.4  5730.4  5732.2    5790
   88.21   87.55   87.33      88    88.4    89.2    88.5    88.2   86.61   86.31
   85.96   87.11   87.21   86.21   85.71   85.86   85.95   86.32    86.4   86.19
   86.12    86.3   86.71   89.71   89.71   89.71   89.76   89.76   86.76   86.76
   86.44    86.3   86.38    86.7   86.19   86.11   86.11   86.61   86.31   85.91
   86.21   85.91   86.01      86
    88.2    87.4   87.32   87.29   87.05   86.81   86.75   86.64    86.6    86.3
    85.7    87.1    87.2    86.2    85.7   85.85   85.86   86.31   86.22   86.18
   86.11    86.1   85.86   85.82   85.75   84.82   84.85   85.96   85.99   86.04
   86.07   86.29   86.37   86.69   86.18    86.1    86.1    86.6    86.3    85.9
    86.2    85.9      86      86
  2769.3  2879.3  2956.1  2986.1  3216.1  3456.1  3516.1  3616.1  3656.1  3949.3
  3969.3  4009.3  4109.3  4180.4  4260.4  4835.9  4870.5    4889  4915.9  4925.9
  4945.9  4950.2 4950.97 4951.08 4951.31  4951.4 5055.89    5056 5056.11  5056.3
  5056.4  5057.2  5057.5  5090.4  5112.9  5140.4  5280.4  5370.4  5660.4  5680.4
  5710.4  5730.4  5732.2    5790
   88.21   87.55   87.33      88    88.4    89.2    88.5    88.2   86.61   86.31
   85.96   87.11   87.21   86.21   85.71   85.86   85.95   86.32    86.4   86.19
   86.12    86.3   86.71   89.71   89.71   89.71   89.76   89.76   86.76   86.76
   86.44    86.3   86.38    86.7   86.19   86.11   86.11   86.61   86.31   85.91
   86.21   85.91   86.01      86
    88.2    87.4   87.32   87.29   87.05   86.81   86.75   86.64    86.6    86.3
    85.7    87.1    87.2    86.2    85.7   85.85   85.86   86.31   86.22   86.18
   86.11    86.1   85.86   85.82   85.75   84.82   84.85   85.96   85.99   86.04
   86.07   86.29   86.37   86.69   86.18    86.1    86.1    86.6    86.3    85.9
    86.2    85.9      86      86
Pier Skew, UpSta & Num, DnSta & Num=  ,4986.2, 2 ,4986.2, 2 , 0 , 0 , 0 ,,
       1       1
   72.84   85.83
       1       1
   73.11    86.1
Pier Skew, UpSta & Num, DnSta & Num=  ,5021.5, 2 ,5021.5, 2 , 0 , 0 , 0 ,,
       1       1
   75.24   85.84
       1       1
   75.51   86.11
Abutment Skew #Up #Dn= , 2 , 2
  4951.2  4990.9
   85.72   71.94
  4951.2  4990.9
   85.99   72.21
Abutment Skew #Up #Dn= , 2 , 2
  5009.1 5056.39
   71.84   86.01
  5009.1 5056.39
   72.11   86.28
BR Coef= 1 , 1 , 0 ,1.25, 0 ,,,0.8,0,2,0,
WSPro=,,,, 1 ,,,, 0 ,,,, 0 ,,,,-1 ,-1 ,-1 , 0 , 0 , 0 , 0 , 0
BC Design=,, 0 ,, 0 ,,,,,,
BC HTab HWMax=88.2

Type RM Length L Ch R = 1 ,19290   ,227.7,213,182.9
BEGIN DESCRIPTION:
Guhn - 2
END DESCRIPTION:
XS GIS Cut Line= 4
      3072464.97      13878260.2      3072859.37     13876419.07
      3072911.38     13874880.72 3072912.998015813874774.0998397
#Sta/Elev= 30
  2296.1   88.13  2769.3   88.44  2879.3   87.64  3949.3   86.54  3969.3   85.94
  4009.3   87.34  4109.3   87.44  4180.4   86.44  4260.4   85.94  4365.9   85.97
  4950.2   86.34  4964.4   81.88  4986.1   75.06  4990.8   72.23  4993.4   71.31
  5007.6   71.68  5009.1   72.08  5017.6   76.62  5027.1   78.27  5057.5   86.61
  5084.4   86.87  5140.4   86.34  5280.4   86.34  5370.4   86.84  5660.4   86.32
  5680.4    85.9  5712.3   86.23  5722.3   85.83  5762.3    87.5    5825   88.27
#Mann= 4 ,-1 , 0
  2296.1     .99       0  4365.9     .06       0  4964.4     .04       0
  5084.4     .06       0
#XS Ineff= 2 , 0
       0 4954.06   85.91 5051.96       0   85.91
Permanent Ineff=
       F       F
Bank Sta=4950.2,5057.5
Exp/Cntr=0.5,0.3