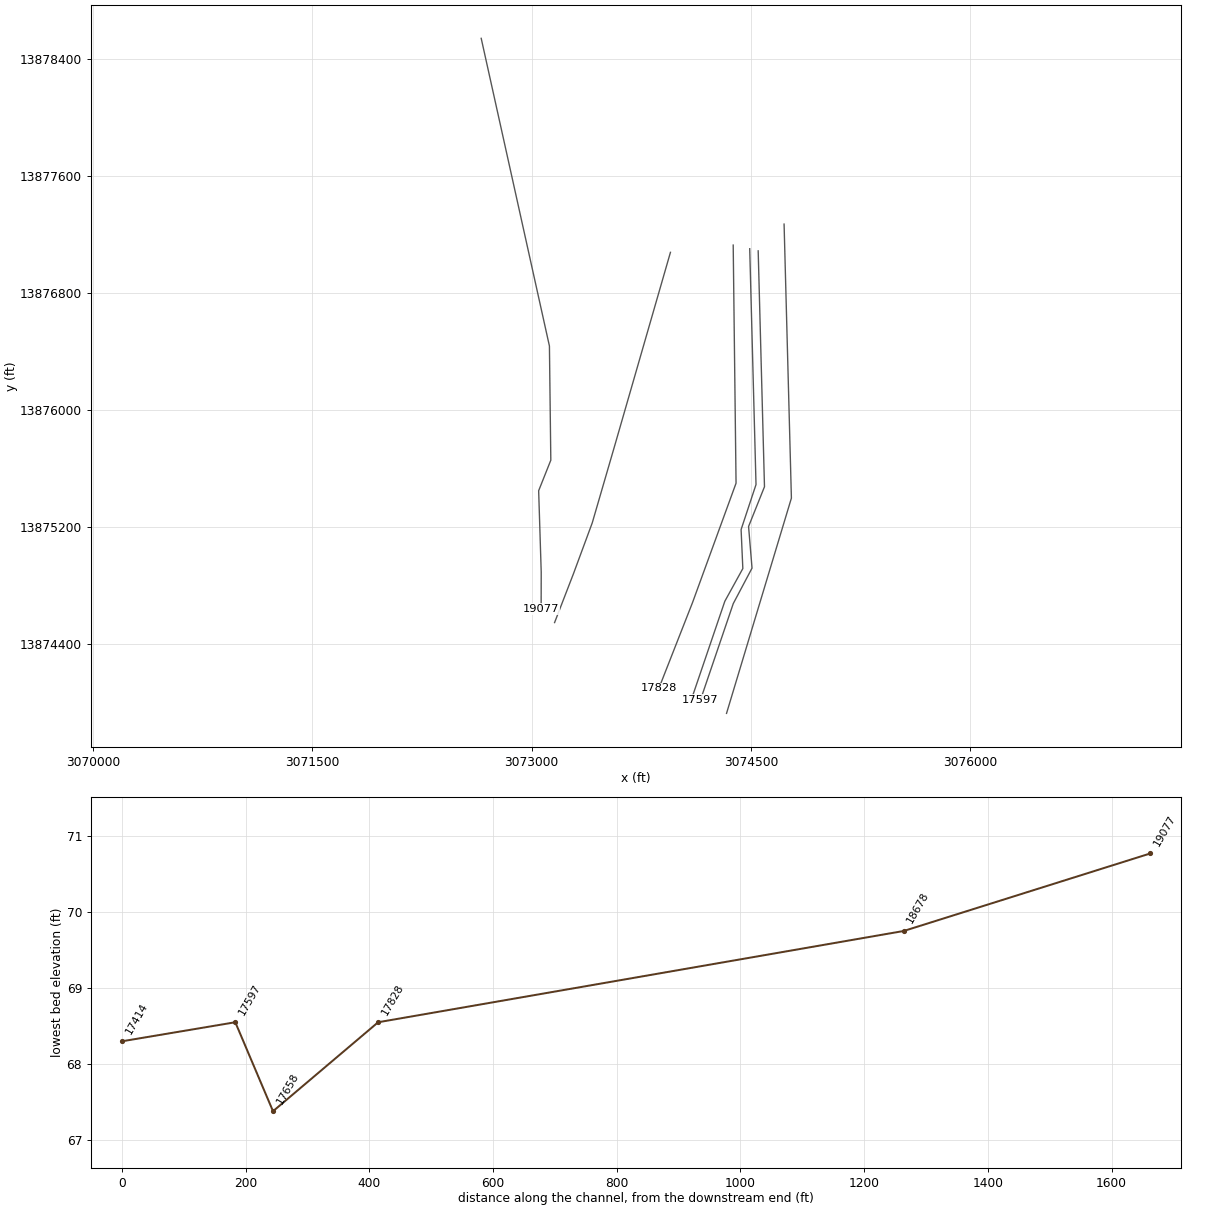
HEC-RAS study E117-00-00.prj: E117-00-00

--- E117-00-00.g02 (geometry) --- (continued)

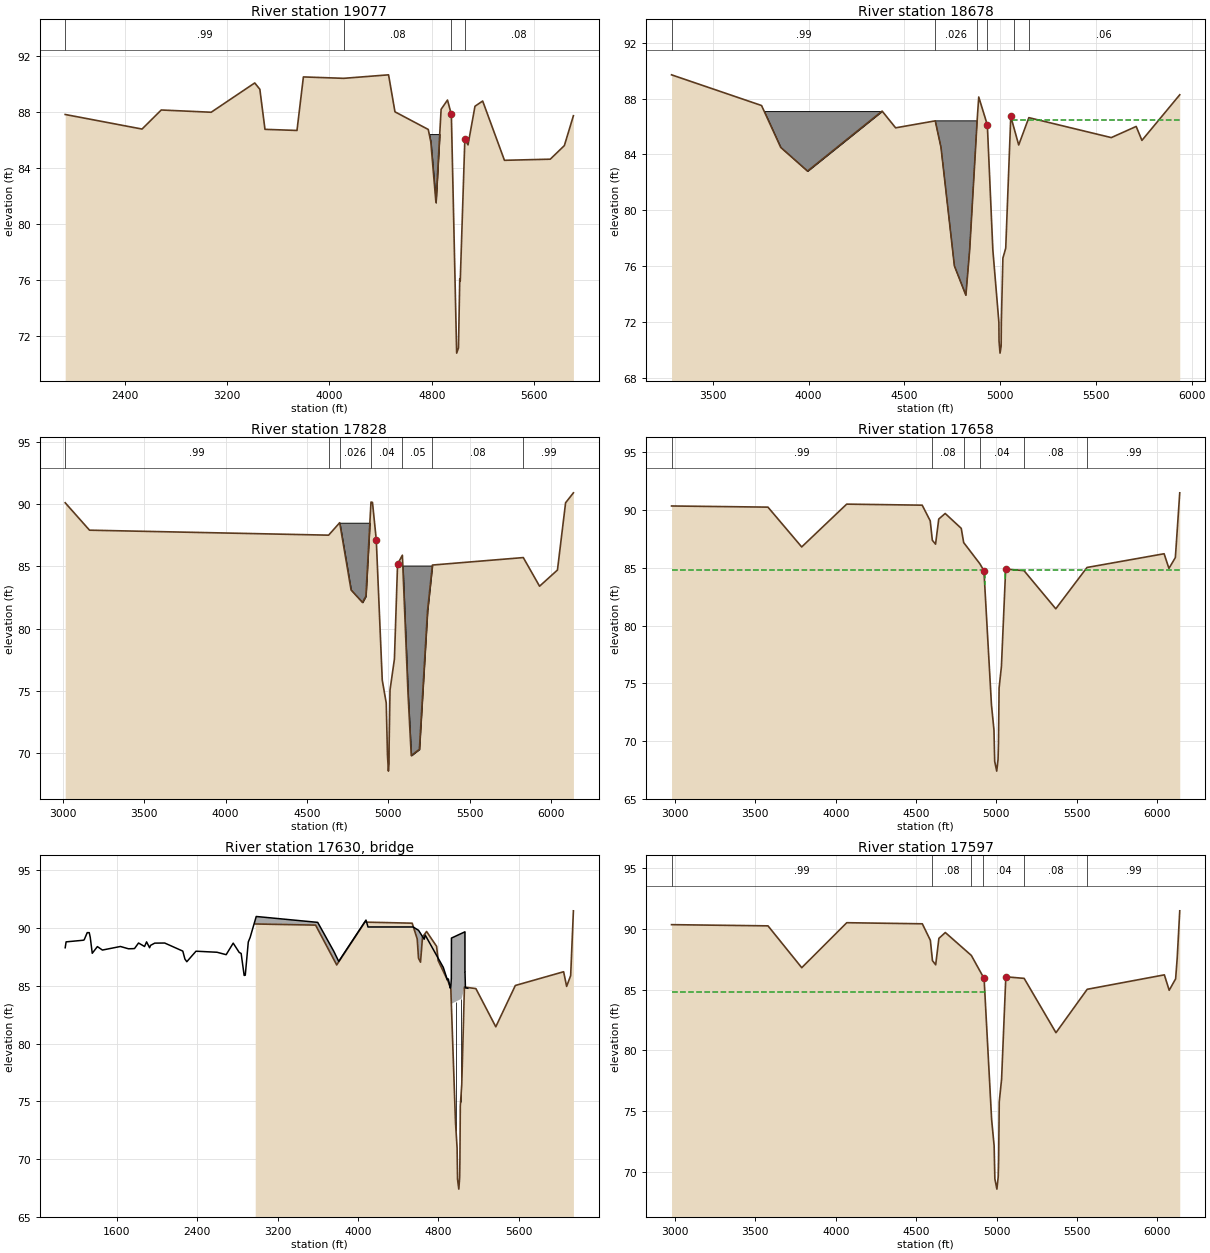
Type RM Length L Ch R = 1 ,19077   ,401.9,399,409.3
BEGIN DESCRIPTION:
Guhn - 1
Interpolated channel, LIDAR overbanks
END DESCRIPTION:
XS GIS Cut Line= 6
      3072655.48       13878542.      3073121.87     13876438.47
      3073131.33     13875658.23      3073048.23     13875449.58
      3073065.76     13874892.02      3073065.15     13874641.29
#Sta/Elev= 30
  1936.6    87.8  2536.6   86.76  2686.6   88.12  3076.6   87.96  3416.6   90.05
  3456.6    89.6  3496.6   86.74  3746.6   86.66  3796.6   90.48  4111.7   90.38
  4461.7   90.63  4511.7   87.99  4771.7   86.73  4791.7   85.84  4831.7   81.51
    4872   88.17    4922   88.83    4952    87.8  4993.4   70.77  5007.6   71.14
  5017.6   76.08  5021.5   75.92  5057.5   86.07    5082   85.63  5136.6   88.39
  5196.6   88.76  5366.6   84.53  5724.4   84.61  5834.4   85.58  5905.1   87.71
#Mann= 4 ,-1 , 0
  1936.6     .99       0  4111.7     .08       0    4952     .04       0
  5057.5     .08       0
#XS Ineff= 2 , 0
       0                 5161.47       0   86.45
Permanent Ineff=
       F       F
#Block Obstruct= 1 ,-1
    4600    4900    86.4
Bank Sta=4952,5057.5
Exp/Cntr=0.3,0.1

Type RM Length L Ch R = 1 ,18678   ,849.5,850,841.8
BEGIN DESCRIPTION:
Cross Section XS14
Left overbank has a detention pond;
Located At: DS GUHN
END DESCRIPTION:
XS GIS Cut Line= 5
      3073949.1413877079.1044595      3073573.22      13875775.2
      3073414.54     13875229.66      3073285.89     13874881.59
      3073157.08      13874548.2
#Sta/Elev= 30
  3284.3    89.7  3754.3    87.5  3854.3    84.5  3994.3    82.8    4384    87.1
  4454.3    85.9  4661.3    86.4  4691.3    84.5  4761.3      76  4821.3    73.9
  4841.3    77.2  4881.3    86.7  4888.4   88.11  4933.3   86.11  4962.1   77.14
  4993.6   71.96  4994.4   70.62  4999.6   69.75  5005.4   70.25  5006.4   71.97
  5014.5   76.56  5029.3   77.27  5055.7   86.72  5074.4   85.79  5097.1   84.67
    5150   86.63  5580.5    85.2  5710.5      86  5740.5      85    5938   88.27
#Mann= 6 ,-1 , 0
  3284.3     .99       0  4661.3    .026       0  4881.3     .05       0
  4933.3     .04       0  5074.4     .05       0    5150     .06       0
#XS Ineff= 2 , 0
                         5061.47           86.45
Permanent Ineff=
       F       F
#Block Obstruct= 2 ,-1
 3710.03 4380.76    87.1    4661    4880    86.4
Bank Sta=4933.3,5055.7
Exp/Cntr=0.3,0.1

Type RM Length L Ch R = 1 ,17828   ,140.9,170,192.9
BEGIN DESCRIPTION:
Alamo - 4
Cross Section XS13; Right overbank has a small online detention pond.  Left ovrbank has a small offline detention pond
Located At: 2ND US HOLLISTER
END DESCRIPTION:
XS GIS Cut Line= 4
      3074378.14     13877128.69       3074397.6     13875501.14
      3074099.98      13874684.8      3073870.55     13874100.06
#Sta/Elev= 30
  3013.9    90.1  3163.4    87.9  4633.4    87.5  4701.6    88.5  4771.6    83.1
  4841.6    82.1  4862.7    82.6    4894   90.16  4903.2   90.13  4926.5   87.14
  4963.3   75.86  4987.8   74.02  4995.3   69.87  5001.1   68.55  5004.9   69.13
  5005.5   70.67  5011.1   75.07  5038.1   77.55  5057.4   85.17    5087   85.89
  5121.6    74.8  5141.6    69.8  5191.6    70.3  5241.6    81.4  5271.6    85.1
  5830.5    85.7  5930.5    83.4  6040.5    84.7  6090.5    90.1  6138.6    90.9
#Mann= 7 ,-1 , 0
  3013.9     .99       0  4633.4     .05       0  4701.6    .026       0
    4894     .04       0    5087     .05       0  5271.6     .08       0
  5830.5     .99       0
#Block Obstruct= 2 ,-1
 4701.63    4889    88.5 5078.06  5271.9   85.06
Bank Sta=4926.5,5057.4
Exp/Cntr=0.5,0.3

Type RM Length L Ch R = 1 ,17658   ,56.5,61,61.5
BEGIN DESCRIPTION:
Alamo - 3
Right overbank has ditch that drains to E117
END DESCRIPTION:
XS GIS Cut Line= 6
        3074491.13877103.6998798      3074534.08     13875491.71
      3074432.11     13875184.08      3074443.98     13874917.41
      3074320.89     13874693.96 3074096.224367113874033.9752607
#Sta/Elev= 30
  2978.3   90.36  3578.3   90.26  3788.3   86.81  4068.3   90.52  4538.3   90.43
  4588.3   89.07  4601.4   87.39  4621.4   87.05  4641.4   89.23  4681.4   89.71
  4781.4   88.42  4796.4   87.19  4897.8   85.34  4922.5   84.75  4969.4   73.12
    4985   70.95  4989.5   68.23  5002.1   67.38  5010.4   68.39    5013   69.82
  5016.8   74.58  5031.3   76.44  5057.7   84.89  5171.7   84.76  5369.6   81.45
  5563.9   85.03  6043.9   86.22  6073.9   84.95  6113.9   85.89  6141.2    91.5
#Mann= 6 ,-1 , 0
  2978.3     .99       0  4601.4     .08       0  4796.4     .05       0
  4897.8     .04       0  5171.7     .08       0  5563.9     .99       0
#XS Ineff= 2 , 0
       0 4927.45    84.8 5054.99       0    84.8
Permanent Ineff=
       F       F
Bank Sta=4922.5,5057.7
Exp/Cntr=0.5,0.3

Type RM Length L Ch R = 3 ,17630   ,,,
BEGIN DESCRIPTION:
ALAMO DRIVE
Structure ID: E117-00-00-10
END DESCRIPTION:
Bridge Culvert--1,0,-1,-1, 0
Deck Dist Width WeirC Skew NumUp NumDn MinLoCord MaxHiCord MaxSubmerge Is_Ogee
10,36,2.6,0, 58, 58, , , 0.95, 0, ,,,
  1089.3  1098.2  1268.2  1278.2  1308.2  1328.2  1338.2  1358.2  1409.3  1459.3
  1638.2  1718.2  1758.2  1778.2  1818.2  1878.2  1898.2  1928.2  1938.2  1979.3
  2078.2  2258.2  2279.3  2298.2  2389.3  2598.2  2689.3  2759.3  2819.3  2838.2
  2868.2  2879.3  2909.3  2928.2  2988.2  3599.3  3758.2  3808.2  4079.3  4099.3
  4547.8  4601.9  4657.8  4667.8  4847.8  4887.8  4897.8  4915.4  4917.8  4922.5
  4927.5  4928.9  5057.7 5063.07 5063.18  5063.5  5067.8  5091.6
    88.3   88.81   88.95   88.99   89.61   89.61   89.21   87.82    88.4    88.1
   88.41   88.21   88.22   88.23   88.71   88.41   88.81    88.3   88.51    88.7
   88.71   88.01   87.32   87.09      88   87.91    87.7    88.7   87.89   87.81
    85.9   85.92    88.8   89.21   91.01    90.5   88.01   87.12    90.7    90.1
    90.1   89.81   89.04    89.4    86.6   85.52    85.6   84.86    84.8   84.94
   85.63   89.14   89.66   89.68   86.18   86.18   84.82   84.79
       0       0       0       0       0       0       0       0       0       0
       0       0       0       0       0       0       0       0       0       0
       0       0       0       0       0       0       0       0       0       0
       0       0       0       0       0       0       0       0       0       0
       0       0       0       0       0       0       0   84.85   84.79   84.68
   83.44   83.44      84   84.81   84.81   84.81   84.81   84.78
  1089.3  1098.2  1268.2  1278.2  1308.2  1328.2  1338.2  1358.2  1409.3  1459.3
  1638.2  1718.2  1758.2  1778.2  1818.2  1878.2  1898.2  1928.2  1938.2  1979.3
  2078.2  2258.2  2279.3  2298.2  2389.3  2598.2  2689.3  2759.3  2819.3  2838.2
  2868.2  2879.3  2909.3  2928.2  2988.2  3599.3  3758.2  3808.2  4079.3  4099.3
  4547.8  4601.9  4657.8  4667.8  4847.8  4887.8  4897.8  4915.4  4917.8  4922.5
  4927.5  4928.9  5057.7 5063.07 5063.18  5063.5  5067.8  5091.6
    88.3   88.81   88.95   88.99   89.61   89.61   89.21   87.82    88.4    88.1
   88.41   88.21   88.22   88.23   88.71   88.41   88.81    88.3   88.51    88.7
   88.71   88.01   87.32   87.09      88   87.91    87.7    88.7   87.89   87.81
    85.9   85.92    88.8   89.21   91.01    90.5   88.01   87.12    90.7    90.1
    90.1   89.81   89.04    89.4    86.6   85.52    85.6   84.86    84.8   84.94
   85.63   89.14   89.66   89.68   86.18   86.18   84.82   84.79
       0       0       0       0       0       0       0       0       0       0
       0       0       0       0       0       0       0       0       0       0
       0       0       0       0       0       0       0       0       0       0
       0       0       0       0       0       0       0       0       0       0
       0       0       0       0       0       0       0   84.85   84.79   84.68
   83.44   83.44      84   84.81   84.81   84.81   84.81   84.78
Pier Skew, UpSta & Num, DnSta & Num=  ,4974.3, 2 ,4974.3, 2 , 0 , 0 , 0 ,,
     1.3     1.3
   71.95   84.62
     1.3     1.3
    73.2   85.87
Pier Skew, UpSta & Num, DnSta & Num=  ,5019.7, 2 ,5019.7, 2 , 0 , 0 , 0 ,,
     1.3     1.3
      73   84.81
     1.3     1.3
   74.25   86.06
BR Coef= 1 , 1 , 0 ,1.25, 0 ,,,0.8,-1,2,0,
WSPro=,,,, 1 ,,,, 0 ,,,, 0 ,,,,-1 ,-1 ,-1 , 0 , 0 , 0 , 0 , 0
BC Design=,, 0 ,, 0 ,,,,,,
BC HTab HWMax=91.5

Type RM Length L Ch R = 1 ,17597   ,210.8,183,161.3
BEGIN DESCRIPTION:
Alamo - 2
Right overbank has ditch that drains to E117
END DESCRIPTION:
XS GIS Cut Line= 6
      3074548.89      13877089.2      3074591.97     13875476.67
       3074483.2     13875205.13      3074506.81     13874920.49
      3074378.55       13874678.      3074154.35     13874019.38
#Sta/Elev= 30
  2978.3   90.36  3578.3   90.26  3788.3   86.81  4068.3   90.52  4538.3   90.43
  4588.3   89.07  4601.4   87.39  4621.4   87.05  4641.4   89.23  4681.4   89.71
  4843.3   87.82  4915.4   86.09  4922.5   85.92  4969.4   74.29    4985   72.12
  4989.5    69.4  5002.1   68.55  5010.4   69.56    5013   70.99  5016.8   75.75
  5031.3   77.61  5057.7   86.06  5171.7   85.93  5369.6   81.45  5563.9   85.03
  6043.9   86.22  6073.9   84.95  6113.9   85.89  6123.9   87.63  6139.6    91.5
#Mann= 6 ,-1 , 0
  2978.3     .99       0  4601.4     .08       0  4843.3     .05       0
  4915.4     .04       0  5171.7     .08       0  5563.9     .99       0
#XS Ineff= 2 , 0
       0 4927.45    84.8 5054.99       0    84.8
Permanent Ineff=
       F       F
Bank Sta=4922.5,5057.7
Exp/Cntr=0.5,0.3

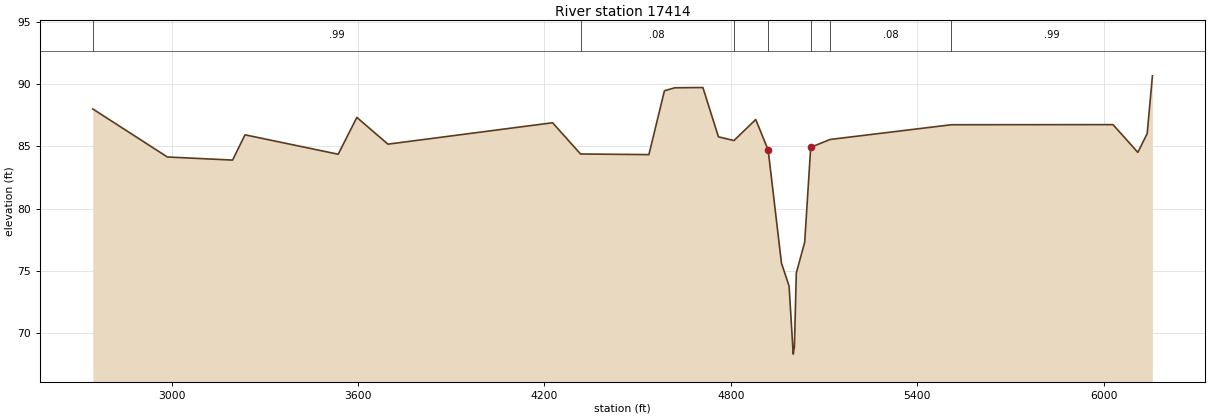
Type RM Length L Ch R = 1 ,17414   ,635.3,641,644.4
BEGIN DESCRIPTION:
Alamo - 1
Interpolated channel, LIDAR overbanks
END DESCRIPTION:
XS GIS Cut Line= 4
      3074725.94      13877272.1      3074732.35      13877032.2
      3074775.98     13875399.04       3074332.5     13873927.52
#Sta/Elev= 30
  2746.2      88  2986.2   84.14  3196.2   83.89  3236.2   85.92  3536.2   84.36
  3596.2   87.32  3696.2   85.17  4226.2   86.89  4316.2   84.38  4536.2   84.33
  4586.2   89.46    4620    89.7    4710   89.72    4760   85.76    4810   85.46
    4880   87.15    4920   84.71  4962.9   75.61  4987.4   73.77  5000.7    68.3
  5004.5   68.88  5010.7   74.82  5037.7    77.3    5057   84.92    5120   85.55
    5510   86.73    6030   86.74    6110   84.51    6140   86.02  6156.9   90.66
#Mann= 7 ,-1 , 0
  2746.2     .99       0  4316.2     .08       0    4810     .05       0
    4920     .04       0    5057     .04       0    5120     .08       0
    5510     .99       0
Bank Sta=4920,5057
Exp/Cntr=0.3,0.1